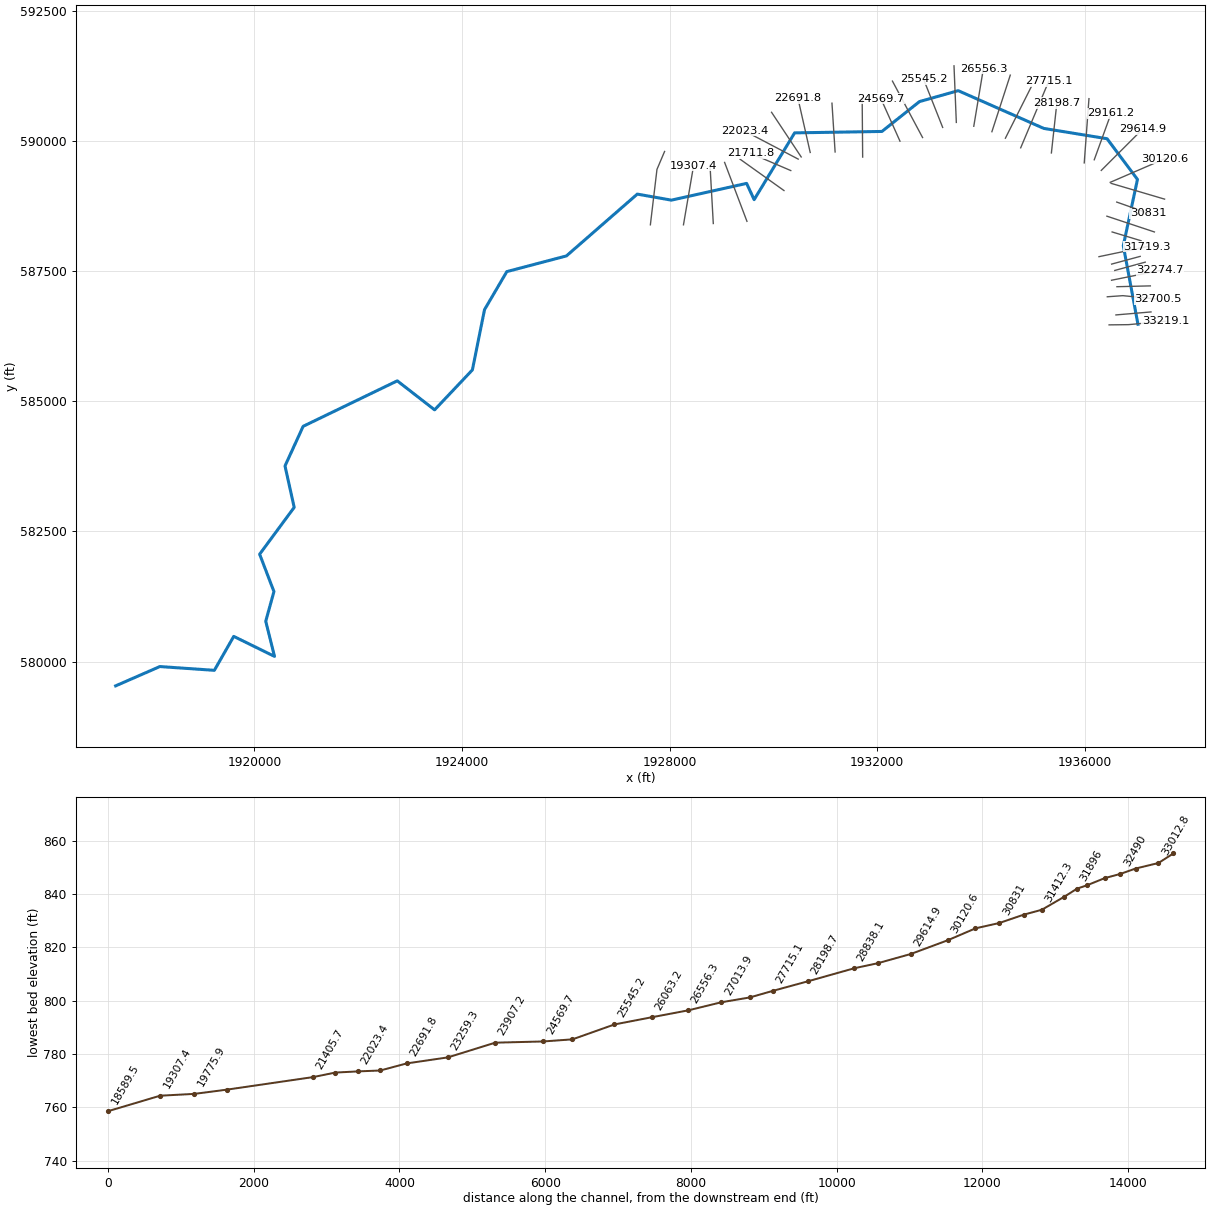
--- MFBgSndyCk.prj (project) ---

Proj Title=MFBgSndyCk
Current Plan=p01
Default Exp/Contr=0,0
English Units
Geom File=g01
Flow File=f01
Plan File=p01
BEGIN DESCRIPTION:
AMEC Environment & Infrastructure, 2013
Projection: NAD 1983 State Plane West Virginia South FIPS 4702 (US Feet)
Vertical Datum: NAVD 1988
END DESCRIPTION:
DSS Export Rating Curves= 0
DSS Export Rating Curve Sorted= 0
DSS Export Volume Flow Curves= 0
DXF OffsetX= 0
DXF OffsetY= 0
DXF ScaleX= 0
DXF ScaleY= 0

--- MFBgSndyCk.p01 (plan) ---

Plan Title=Floodplain
Program Version=4.00
Geom File=g01
Flow File=f01
K Sum by GR=0
Std Step Tol=0.01
Critical Tol=0.01
Num of Std Step Trials=20
Max Error Tol=0.3
Flow Tol Ratio=0.001
Split Flow NTrial=30
Split Flow Tol=0.02
Split Flow Ratio=0.02
Log Output Level=0
Friction Slope Method=1
Unsteady Friction Slope Method=2
Unsteady Bridges Friction Slope Method=1
Global Log Level=0
CheckData=False
Run HTab=0
Run UNet=0
Run PostProcess=0
UNET Theta=0
UNET Theta Warmup=0
UNET ZTol=0
UNET ZSATol=0
UNET MxIter=0
UNET MaxInSteps=0
UNET DtIC=0
UNET DtMin=0
UNET MaxCRTS=0
UNET WFStab=0
UNET SFStab=0
UNET WFX=0
UNET SFX=0
UNET DSS MLevel=0
UNET DZMax Abort=0
UNET Convert EG Bridges=0
UNET Use Existing IB Tables=0
UNET Froude Limit=0
UNET Froude Power=0
Write IC File=0
Echo Input=False
Echo Output=False
Write Detailed=0

--- MFBgSndyCk.f01 (steady flow) ---

Flow Title=NFF Regression Equation
Program Version=4.10
Number of Profiles= 1
Profile Names=P100yr
River Rch & RM=MFBgSndyCk,Main            ,33219.1
922.3438
River Rch & RM=MFBgSndyCk,Main            ,30501.7
974.7829
River Rch & RM=MFBgSndyCk,Main            ,30120.6
1296.954
River Rch & RM=MFBgSndyCk,Main            ,29614.9
1371.412
River Rch & RM=MFBgSndyCk,Main            ,27715.1
1448.743
River Rch & RM=MFBgSndyCk,Main            ,27403.5
1615.266
River Rch & RM=MFBgSndyCk,Main            ,24968.6
 1705.95
River Rch & RM=MFBgSndyCk,Main            ,22023.4
1894.585
River Rch & RM=MFBgSndyCk,Main            ,18123.3
2099.241
River Rch & RM=MFBgSndyCk,Main            ,17656.7
2337.621
River Rch & RM=MFBgSndyCk,Main            ,13930.7
2463.998
River Rch & RM=MFBgSndyCk,Main            ,4296.2
2737.248
River Rch & RM=MFBgSndyCk,Main            ,3522.5
3082.938
River Rch & RM=MFBgSndyCk,Main            ,404.5
3118.366
River Rch & RM=MFBgSndyCk,Main            ,92
6442.896
Boundary for River Rch & Prof#=MFBgSndyCk,Main            , 1
Up Type= 0
Dn Type= 1
Dn Known WS=722.73
DSS Import GetInterval= 0
DSS Import GetPeak= 0
DSS Import FillOption= 0

--- MFBgSndyCk.g01 (geometry) ---

Geom Title=USGS 3m DEM
Program Version=4.10

River Reach=MFBgSndyCk      ,Main
Reach XY= 30
     1937026.358      586482.478     1936743.478      587992.359
     1937016.655      589265.795     1936430.532      590047.901
     1935212.716      590245.619     1933562.728      590971.144
     1932815.565      590761.355     1932092.618      590187.554
     1930410.048      590160.251     1929629.998      588876.903
      1929484.41      589189.617     1928035.977      588867.304
     1927378.276      588983.469     1926012.304      587795.468
     1924863.809      587493.902     1924434.244      586762.993
     1924200.388      585604.986     1923472.299      584837.598
     1922753.002      585395.111        1920939.      584521.034
     1920589.638      583759.251      1920766.77       582963.78
     1920100.609       582063.47     1920376.359      581345.931
      1920218.17      580775.558      1920387.33      580099.753
     1919601.811      580484.354     1919227.915      579832.142
     1918177.538       579904.52     1917325.712      579533.495

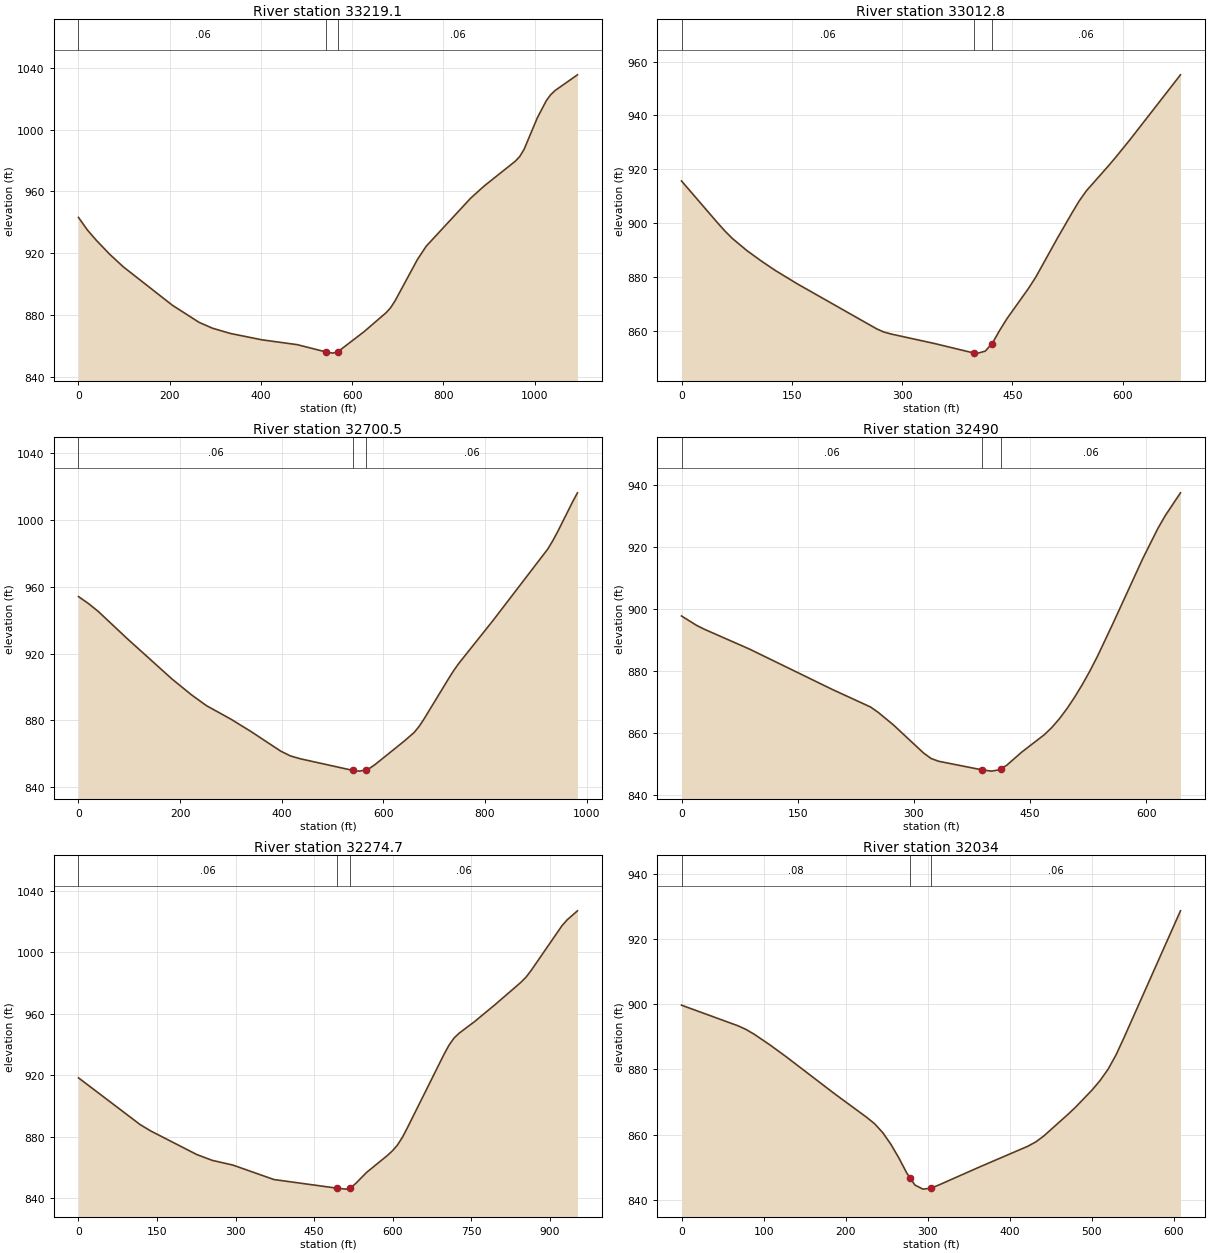
Type RM Length L Ch R = 1 ,33219.1 ,206.4,206.2,206
XS GIS Cut Line= 3
     1936469.646      586470.621     1936841.928      586474.872
     1937560.649      586540.223
#Sta/Elev= 30
       0  943.18    19.6  935.02    39.2  928.33    68.6  919.26      98  911.24
   205.8   886.3   264.5  875.19   293.9   871.4   333.1  868.01   401.6  863.92
   479.6  860.76   543.7  855.96   557.6  855.27   568.7  856.16   625.9   869.1
   674.6  881.48   684.4   884.7   694.1  889.12   742.9  915.78   762.4  924.52
   859.9  955.64   889.2  963.45   957.5  979.53   967.2  982.51     977  987.26
  1006.2 1007.79  1025.7 1018.77  1035.5 1022.73  1045.2 1025.42    1094 1035.54
#Mann= 3 , 0 , 0
       0     .06       0   543.7    .045       0   568.7     .06       0
Bank Sta=543.7,568.7
XS Rating Curve= 0 ,0
Exp/Cntr=0.3,0.1

Type RM Length L Ch R = 1 ,33012.8 ,317.1,312,306.9
XS GIS Cut Line= 2
     1936601.619      586661.842     1937277.653      586719.241
#Sta/Elev= 30
       0  915.62    49.2  900.02      59  897.04    68.8  894.35    88.5  889.85
   108.2  885.94   127.8  882.33   157.3  877.43   265.5  860.66   275.3  859.49
   285.2  858.75   344.2  855.22   393.3  851.98   397.1  851.86   403.2  851.66
     413  852.39   422.1  855.18   422.8   855.4   432.6   860.1   442.5  864.44
     472  875.76   481.8  879.93   511.3  894.44     531  903.76   540.8   908.2
   550.6  911.98   580.1   921.1     590  924.28   609.6  930.87   678.5  955.06
#Mann= 3 , 0 , 0
       0     .06       0   397.1    .045       0   422.1     .06       0
Bank Sta=397.1,422.1
XS Rating Curve= 0 ,0
Exp/Cntr=0.3,0.1

Type RM Length L Ch R = 1 ,32700.5 ,206.9,210.4,213.8
XS GIS Cut Line= 3
     1936435.202      587010.521     1936734.753      587032.046
      1937412.78      586963.885
#Sta/Elev= 30
       0  954.18    19.4  950.07    38.8  945.31    96.9  928.71   184.1  904.78
   222.8  895.21   251.9  888.81   300.3  880.67   339.3  873.36   397.7  861.63
   417.1  858.71   436.6  856.99   540.7  849.98   553.4   849.6   565.7  850.37
   572.9  851.32   582.6   853.3     641   867.6   660.5  872.77   670.2  876.36
     680  880.88   728.7  905.23   738.4  909.88   748.1  914.04   816.3   940.1
   923.4  982.66   933.1  987.54   942.8  993.01     972 1010.78   981.8 1016.35
#Mann= 3 , 0 , 0
       0     .06       0   540.7    .045       0   565.7     .06       0
Bank Sta=540.7,565.7
XS Rating Curve= 0 ,0
Exp/Cntr=0.3,0.1

Type RM Length L Ch R = 1 ,32490   ,210.6,215.4,220.2
XS GIS Cut Line= 2
     1936620.752      587203.944     1937264.897      587219.888
#Sta/Elev= 30
       0  897.75    19.5  894.71    29.3  893.48    87.9  887.03   195.3  873.92
   244.1  868.31   253.8  866.61   273.4  862.57   312.4  853.47   322.2  851.67
   331.9  850.77   387.8  847.99   400.3  847.57     410  847.98   412.8   848.4
   419.8  849.44   439.3  853.72   468.6  859.37   478.4  861.74   488.1  864.56
   497.9  867.84   507.7  871.52   517.4  875.52   527.2  879.89     537  884.66
   556.5  894.99   595.5  916.25     615  926.01   624.8  930.26   644.3  937.58
#Mann= 3 , 0 , 0
       0     .06       0   387.8    .045       0   412.8     .06       0
Bank Sta=387.8,412.8
XS Rating Curve= 0 ,0
Exp/Cntr=0.3,0.1

Type RM Length L Ch R = 1 ,32274.7 ,238.7,240.3,241.8
XS GIS Cut Line= 2
     1936517.115      587328.309     1937451.444       587516.45
#Sta/Elev= 30
       0  918.37   117.9  887.94   137.6  883.89     226  868.48   255.5  864.69
   294.8  861.65   373.4  852.22   493.5  846.62   510.9  845.99   518.5   846.8
   520.8  847.04   530.6  850.03   550.2  856.82   589.5  867.73   599.4  870.79
   609.2  874.61     619  879.83   628.8  886.24   697.6  933.22   707.4   939.4
   717.3  944.22   727.1  947.39   756.6  954.95   795.9  966.01     845  980.44
   854.8   983.8   864.6  988.16   923.6 1017.31   933.4  1021.1   953.1 1026.98
#Mann= 3 , 0 , 0
       0     .06       0   493.5    .045       0   518.5     .06       0
Bank Sta=493.5,518.5
XS Rating Curve= 0 ,0
Exp/Cntr=0.3,0.1

Type RM Length L Ch R = 1 ,32034   ,139.3,138.1,137.8
XS GIS Cut Line= 2
     1936579.297       587516.45     1937166.043      587675.892
#Sta/Elev= 30
       0  899.71    68.6  893.41    78.4   892.3    88.3  890.84   107.9  887.51
   127.5  883.91   186.3   872.6   225.6  865.34   235.4  863.34   245.2  860.64
     255  857.11   264.8  852.91   274.6   848.2  278.73  846.67   284.4  844.58
   294.2  843.32     304  843.62   313.8  844.61   362.8  850.07   421.7  856.43
   431.5  857.76   441.3  859.58   470.7  866.19   480.5  868.52   500.2  873.68
     510   876.6   519.8  880.06   529.6  884.53   539.4  889.86     608  928.63
#Mann= 3 , 0 , 0
       0     .08       0  278.73    .045       0     304     .06       0
Bank Sta=278.73,304
XS Rating Curve= 0 ,0
Exp/Cntr=0.3,0.1

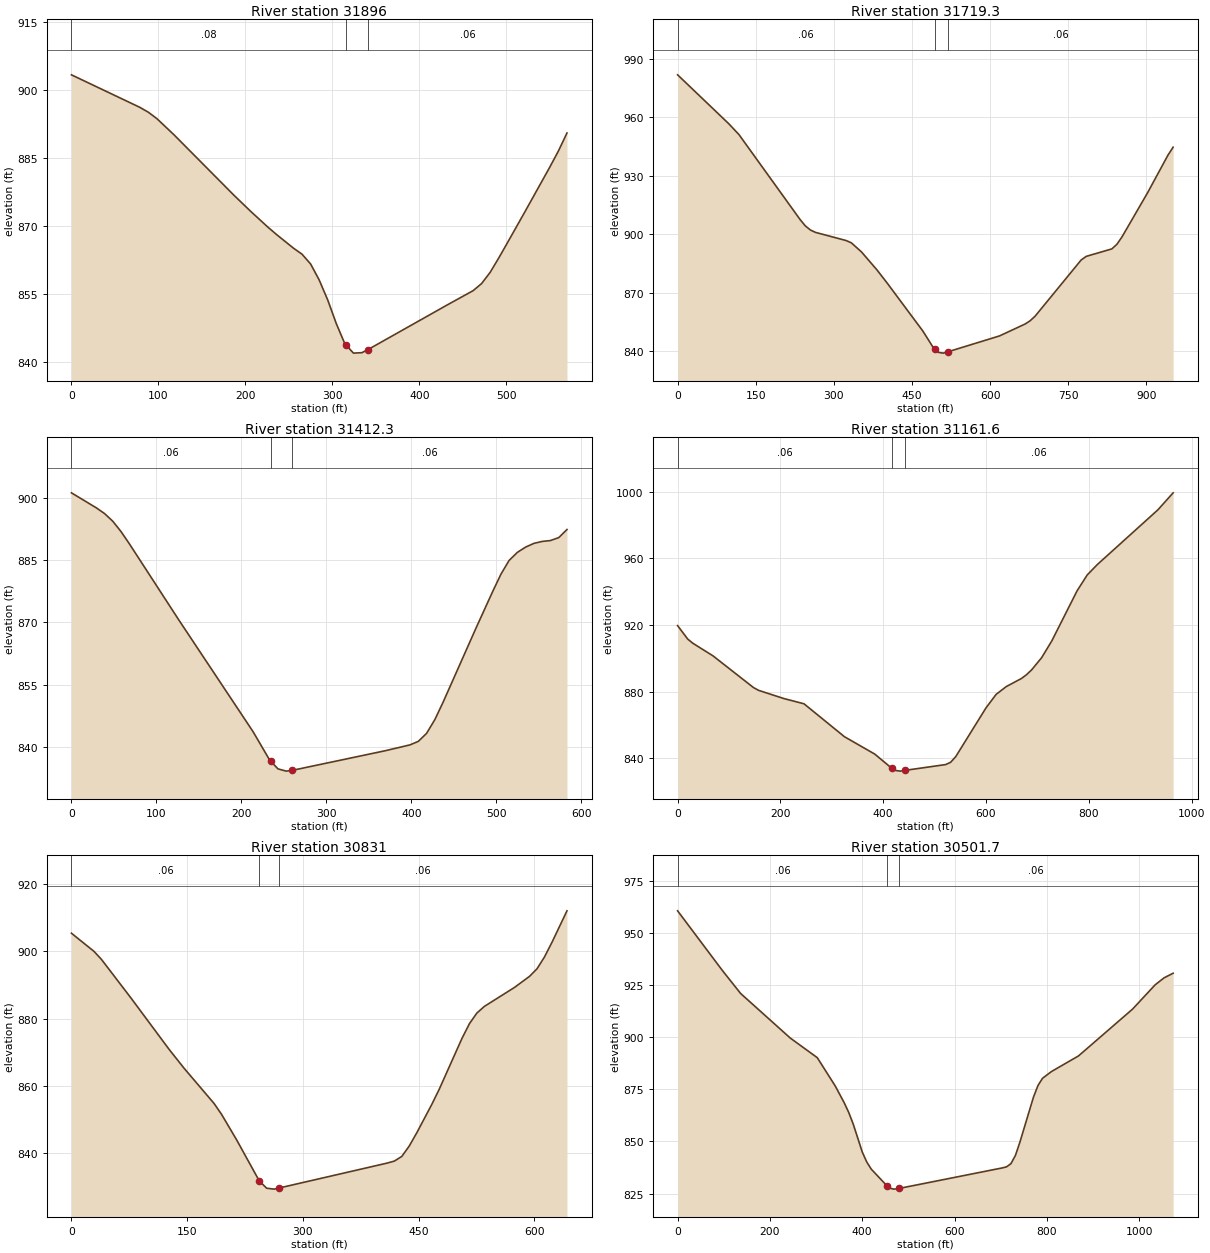
Type RM Length L Ch R = 1 ,31896   ,177.1,176.6,175.2
XS GIS Cut Line= 2
     1936518.754      587638.468     1937068.828      587786.749
#Sta/Elev= 30
       0  903.45    78.6  896.28    88.4   895.2    98.2  893.79   117.9  890.22
   186.6  876.93   206.3  873.29   225.9  869.84   235.7  868.23   255.4  865.19
   265.2  863.86     275  861.71   284.8   858.2   294.7  853.75   304.5  848.56
   314.3  844.12   315.9  843.79   324.2  842.05     334  842.15   340.9  842.83
   432.2   852.7   461.7  855.82   471.5  857.39   481.3  859.85   491.1  862.99
     501  866.32   520.6  872.98   550.1  883.14   559.9  886.66   569.7  890.62
#Mann= 3 , 0 , 0
       0     .08       0   315.9    .045       0   340.9     .06       0
Bank Sta=315.9,340.9
XS Rating Curve= 0 ,0
Exp/Cntr=0.3,0.1

Type RM Length L Ch R = 1 ,31719.3 ,320.8,307,293.2
XS GIS Cut Line= 2
     1936274.763      587781.124     1937205.904      587975.643
#Sta/Elev= 30
       0  981.69    98.1  956.65   117.7  951.09   235.4   907.4   245.2  904.24
     255  902.11   264.8   900.9   323.6  896.71   333.4  895.57     353  890.88
   382.5  881.73   402.1  874.98   470.7  850.35   490.3  842.03   493.3  841.22
   500.1  839.39   509.9  838.99   518.3  839.63   617.8   847.8   666.8  853.88
   676.7  855.57   686.5  858.01   774.7  886.77   784.5  888.61   833.6  892.44
   843.4  894.84   853.2  898.66   902.2  921.24   941.4  940.57   951.2  944.58
#Mann= 3 , 0 , 0
       0     .06       0   493.3    .045       0   518.3     .06       0
Bank Sta=493.3,518.3
XS Rating Curve= 0 ,0
Exp/Cntr=0.3,0.1

Type RM Length L Ch R = 1 ,31412.3 ,251.3,250.5,249.8
XS GIS Cut Line= 2
     1936528.276       588256.26     1937086.322      588087.252
#Sta/Elev= 30
       0  901.23    29.2  897.62    38.9  896.24    48.6  894.39    58.3   891.9
      68  888.99   126.3  870.59   213.8  843.61   233.2   836.8   234.7  836.47
     243  834.67   252.7  834.12   259.7   834.3   369.3  839.04   398.4  840.45
   408.2   841.3   417.9  843.23   427.6  846.53   437.3  850.73   476.2  868.68
   495.6   877.4   505.3  881.58     515  884.93   524.8  886.88   534.5  888.15
   544.2  889.04   553.9  889.51   563.6  889.72   573.4  890.43   583.1  892.38
#Mann= 3 , 0 , 0
       0     .06       0   234.7    .045       0   259.7     .06       0
Bank Sta=234.7,259.7
XS Rating Curve= 0 ,0
Exp/Cntr=0.3,0.1

Type RM Length L Ch R = 1 ,31161.6 ,331,330.5,330.1
XS GIS Cut Line= 2
     1936427.828        588559.2     1937343.024       588256.26
#Sta/Elev= 30
       0  919.64    19.7  911.57    29.5  909.09    68.9  901.48   147.6  882.45
   157.4  880.79   206.6  875.86   245.9   872.7   324.6  852.92   383.6  842.48
     417  833.89     423  832.73   432.8  832.26     442   832.7   521.4  836.19
   531.2  837.58     541  840.93   600.1  870.31   619.7  878.36   639.4  883.04
   668.9  887.89   678.8  890.18   688.6  893.03   708.3  900.43   727.9  910.43
   777.1   940.5   796.8  950.05   816.5  956.31   934.5  989.22     964  999.39
#Mann= 3 , 0 , 0
       0     .06       0     417    .045       0     442     .06       0
Bank Sta=417,442
XS Rating Curve= 0 ,0
Exp/Cntr=0.3,0.1

Type RM Length L Ch R = 1 ,30831   ,327.6,329.2,330.8
XS GIS Cut Line= 2
     1936617.563      588830.251     1937223.442      588616.599
#Sta/Elev= 30
       0  905.41    29.2  900.01    38.9  897.61    77.9  885.89   126.5  870.84
     146  865.19     185  854.66   194.7  851.41   214.2  843.83   243.6  831.58
   253.1  829.44   262.8  829.17   268.6  829.47   408.8   836.9   418.6  837.52
   428.3  838.92     438  842.04   447.8     846   467.2  854.43     477  859.03
   506.2  874.04   515.9  878.44   525.6  881.63   535.4  883.62   574.3  889.25
   593.8  892.55   603.5   894.8   613.2  898.32     623  902.73   642.4  912.08
#Mann= 3 , 0 , 0
       0     .06       0   243.6    .045       0   268.6     .06       0
Bank Sta=243.6,268.6
XS Rating Curve= 0 ,0
Exp/Cntr=0.3,0.1

Type RM Length L Ch R = 1 ,30501.7 ,361.9,380.9,399.9
XS GIS Cut Line= 2
     1936509.196      589189.944     1937539.191      588887.005
#Sta/Elev= 30
       0  960.52    97.6  931.76   136.6   920.9     244  899.57   302.6  890.15
   341.6  876.56   361.1  868.47   370.9  863.82   380.6  858.25   400.2  844.86
   409.9  840.11   419.7  836.69   454.3  828.55   458.7  827.67   468.5  827.14
   479.3  827.45   702.7  837.27   712.5   837.8   722.2  839.35     732  843.33
   741.8  849.78     771  871.24   780.8  876.81   790.6  880.25   810.1  883.51
   868.7     891   985.8  913.44  1034.6  925.05  1054.1  928.42  1073.6  930.61
#Mann= 3 , 0 , 0
       0     .06       0   454.3    .045       0   479.3     .06       0
Bank Sta=454.3,479.3
XS Rating Curve= 0 ,0
Exp/Cntr=0.3,0.1

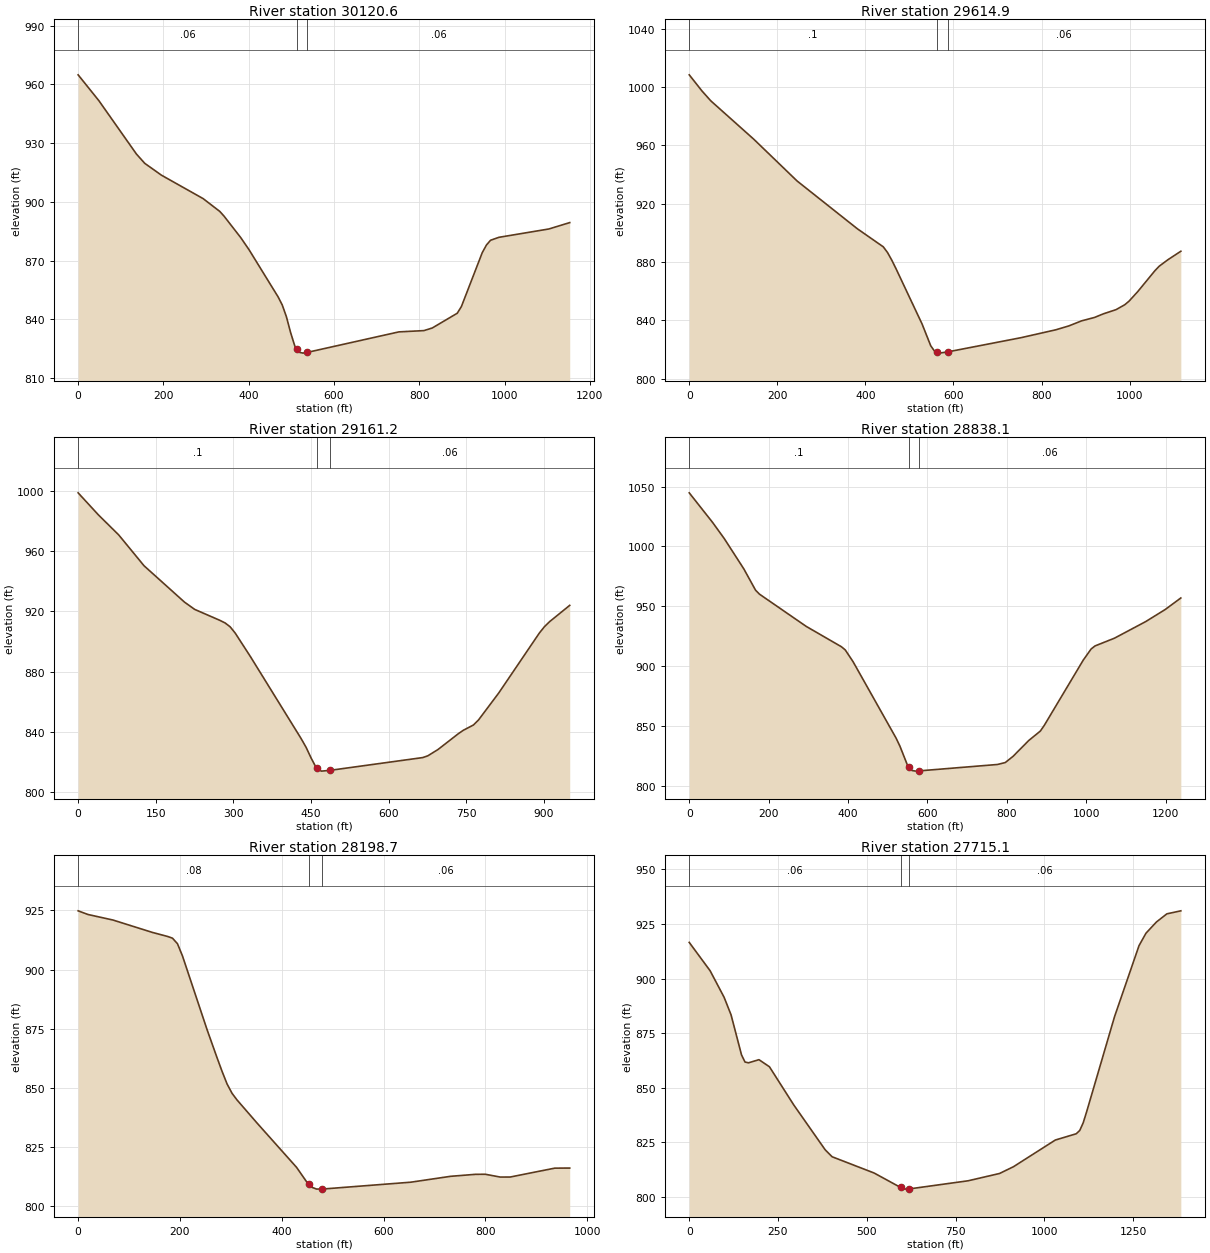
Type RM Length L Ch R = 1 ,30120.6 ,495.3,505.6,516
XS GIS Cut Line= 2
     1936491.604      589209.723     1937550.298      589665.726
#Sta/Elev= 30
       0  964.92    48.8  951.67   136.8  924.41   156.3  919.67   195.4  913.62
   293.1  901.65   332.1  895.12   341.9  892.76     381   881.8   400.5  875.62
   468.9  851.43   478.7  847.25   488.4  841.26   498.2  833.21     508  826.36
  512.61  824.82   517.8  823.12   527.5  822.67   537.3  823.05   752.2  833.53
   810.8  834.18   830.4  835.52     889  843.06   898.7  846.48   947.6  874.02
   957.4  877.92   967.1  880.37   986.6  881.86  1103.9  886.13  1152.7  889.39
#Mann= 3 , 0 , 0
       0     .06       0  512.61    .045       0   537.3     .06       0
Bank Sta=512.61,537.3
XS Rating Curve= 0 ,0
Exp/Cntr=0.3,0.1

Type RM Length L Ch R = 1 ,29614.9 ,441.6,453.7,465.8
XS GIS Cut Line= 2
     1936319.407      589439.319     1937110.239      590226.962
#Sta/Elev= 30
       0 1008.46    29.4  997.23      49  990.61   146.9  964.19   244.8  935.66
   381.8  902.83   440.6  890.47   450.4  886.48   460.2  881.14     470  875.14
   528.7  837.52   548.3   822.6   558.1  818.42   561.8  818.08   567.9  817.53
   586.8  818.37   753.9  828.16   832.2  833.53   861.6  836.16     891  839.68
   920.3  842.01   939.9  844.44   969.3  847.39   988.9  850.72   998.7  853.21
  1018.2  859.68  1057.4   874.1  1067.2  877.19  1086.8   881.6  1116.2  887.43
#Mann= 3 , 0 , 0
       0      .1       0   561.8    .045       0   586.8     .06       0
Bank Sta=561.8,586.8
XS Rating Curve= 0 ,0
Exp/Cntr=0.3,0.1

Type RM Length L Ch R = 1 ,29161.2 ,315.4,323,330.6
XS GIS Cut Line= 2
     1936183.881      589643.405     1936509.143      590536.279
#Sta/Elev= 30
       0  998.48    39.2  983.87    78.4  970.62   127.4  950.16   205.7  926.03
   225.3  921.24   274.3  913.93   284.1  912.26   293.9  909.68   303.7  905.51
   333.1  889.94     431  835.67   440.8  829.76   450.6  822.59   460.4  816.25
   461.4  816.03   470.2  814.06   486.4  814.55   666.2  823.04     676  824.21
   695.6  828.37   734.8  838.81   744.5   841.1   764.1  844.62   773.9  847.93
   813.1  865.85   891.5  905.52   901.3  909.72   911.1  913.02   950.3  923.92
#Mann= 3 , 0 , 0
       0      .1       0   461.4    .045       0   486.4     .06       0
Bank Sta=461.4,486.4
XS Rating Curve= 0 ,0
Exp/Cntr=0.3,0.1

Type RM Length L Ch R = 1 ,28838.1 ,639.9,638.8,637.6
XS GIS Cut Line= 2
     1935990.982      589582.958     1936081.953      590817.924
#Sta/Elev= 30
       0 1044.81      59    1020    88.4 1006.48   137.6  981.19   167.1  963.42
   176.9  960.11   294.8  933.13   383.3  916.15   393.1  913.46   412.8  903.59
   520.9  839.84   530.7  833.07   550.4  816.56   553.8  815.25   560.2  812.77
     570  812.17   578.8  812.37   776.4  817.72   796.1  819.34   815.7  824.53
     855   837.7   884.5  845.69   894.3  850.41   992.6  905.02  1012.3  914.24
  1022.1  916.81  1071.2  923.31  1149.9  937.19    1199  947.28  1238.3  956.91
#Mann= 3 , 0 , 0
       0      .1       0   553.8    .045       0   578.8     .06       0
Bank Sta=553.8,578.8
XS Rating Curve= 0 ,0
Exp/Cntr=0.3,0.1

Type RM Length L Ch R = 1 ,28198.7 ,490.8,483,475.3
XS GIS Cut Line= 2
     1935357.973      589774.147     1935463.204      590733.987
#Sta/Elev= 30
       0  924.85    19.5  923.29    68.3  920.97   146.3   915.7   175.6  914.03
   185.3   913.3   195.1  910.97   204.8  905.89   253.6  874.44   273.1  862.66
   282.8  856.98   292.6  851.68   302.4  847.72   312.1  844.94   351.1  835.26
   429.2  816.42   448.7  810.37   453.1  809.34   458.4  808.09   468.2  807.29
   477.9  807.25   478.1  807.25   653.5  810.18   731.5  812.66   780.3   813.5
   799.8  813.53     829  812.35   848.6  812.36   936.3  816.12   965.6  816.15
#Mann= 3 , 0 , 0
       0     .08       0   453.1    .045       0   478.1     .06       0
Bank Sta=453.1,478.1
XS Rating Curve= 0 ,0
Exp/Cntr=0.3,0.1

Type RM Length L Ch R = 1 ,27715.1 ,313.3,311.3,309.2
XS GIS Cut Line= 2
     1934766.443      589873.001     1935305.357      591148.536
#Sta/Elev= 30
       0  916.62    58.9  903.62    98.2   891.5   117.8  883.46   147.3  865.11
   157.1  861.84     167  861.48   196.4  862.92   225.9  859.68   294.6  842.16
     383  821.65   402.6  818.46   520.5  811.05   595.4  804.41   608.9  803.65
   620.4  803.76   785.6  807.47     874  810.81   913.3  813.91  1031.2  826.13
  1090.1     829  1099.9  830.49  1109.7  834.02  1119.6  839.19  1198.1  882.68
  1266.9  915.12  1286.5  920.82    1316  925.96  1345.4  929.69  1384.7  931.07
#Mann= 3 , 0 , 0
       0     .06       0   595.4    .045       0   620.4     .06       0
Bank Sta=595.4,620.4
XS Rating Curve= 0 ,0
Exp/Cntr=0.3,0.1

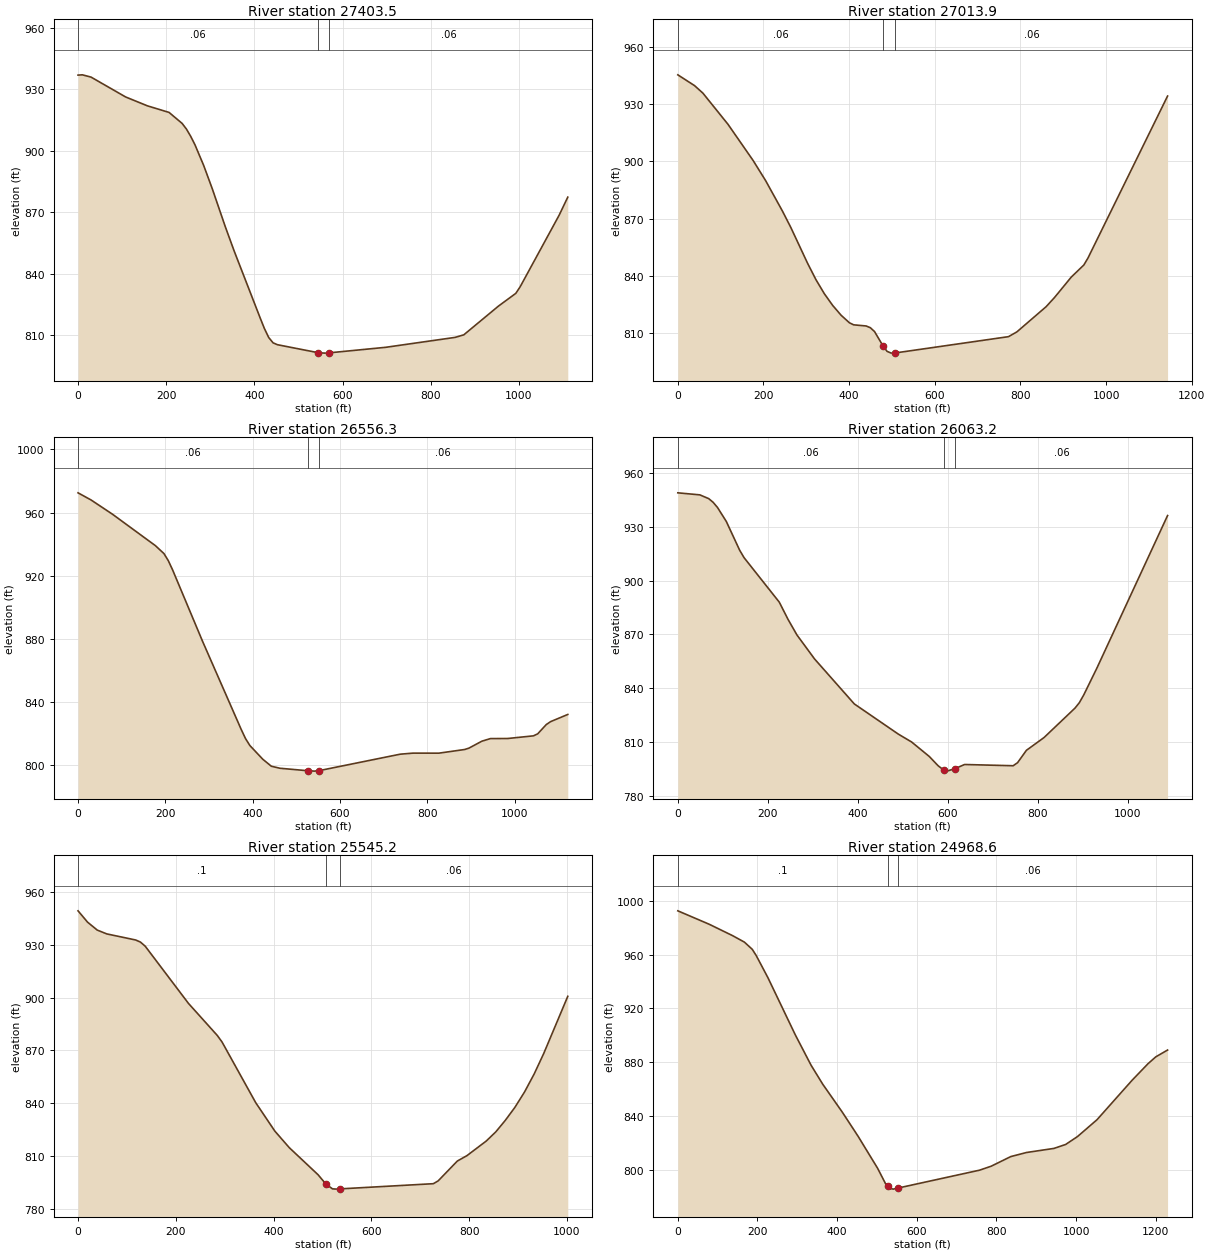
Type RM Length L Ch R = 1 ,27403.5 ,385.4,389.7,394
XS GIS Cut Line= 2
     1934471.476      590057.953     1934972.123      591049.682
#Sta/Elev= 30
       0  936.85     9.8  936.98    29.5  935.87   108.1  926.17   157.3  921.86
   206.5  918.64     236   913.3   245.8  910.55   255.6  906.97   265.4  902.79
   285.1  892.73   304.8  881.24   334.3  862.74   353.9  851.19   412.9  818.52
   422.7  813.25   432.6  808.82   442.4  806.25   452.2  805.33   544.7  801.43
   560.4  801.22   569.7  801.36     698  804.06   855.3   808.9     875  810.14
   953.6  824.15     993  830.38  1002.8  833.56  1091.3   868.5  1110.9  877.31
#Mann= 3 , 0 , 0
       0     .06       0   544.7    .045       0   569.7     .06       0
Bank Sta=544.7,569.7
XS Rating Curve= 0 ,0
Exp/Cntr=0.3,0.1

Type RM Length L Ch R = 1 ,27013.9 ,453.6,457.6,461.6
XS GIS Cut Line= 2
     1934211.586      590182.318     1934565.547      591269.711
#Sta/Elev= 30
       0  945.45    39.1  939.78    58.6  935.84   117.3  919.45   175.9  900.48
   205.2  889.87   244.4  873.92   263.9  865.34     303  846.56   322.5  837.98
   342.1   830.6   361.6  824.45   381.2  819.31   400.7  815.34   410.5  814.26
   439.8  813.66   449.6  812.74   459.4  810.72   478.9  803.28   488.7  800.32
   498.5  799.41   508.2  799.52   772.1  808.05   791.7  810.55   860.1   823.8
   879.7  828.62   918.8  839.33   948.1  845.66   957.8  849.34  1143.6  934.31
#Mann= 3 , 0 , 0
       0     .06       0   478.9    .045       0   508.2     .06       0
Bank Sta=478.9,508.2
XS Rating Curve= 0 ,0
Exp/Cntr=0.3,0.1

Type RM Length L Ch R = 1 ,26556.3 ,487.1,492.5,497.9
XS GIS Cut Line= 2
     1933862.408       590287.55     1934047.361      591394.076
#Sta/Elev= 30
       0  972.52    29.5  968.06    78.7  959.02   177.1  939.12   196.8  934.07
   206.7  929.62   216.5  923.84   285.4  878.45     374  822.63   383.8  816.92
   393.6  812.58   423.2   803.9   442.8  799.46   462.5  798.18   526.3   796.6
   541.3  796.36   551.3  796.62   738.1  807.09   767.6  807.75   826.6  807.73
   885.7  810.05   895.5  810.92   925.1  815.31   944.7  816.96   984.1  817.01
  1043.2  818.69    1053  819.96  1072.7  825.85  1082.5  827.68  1121.9  832.23
#Mann= 3 , 0 , 0
       0     .06       0   526.3    .045       0   551.3     .06       0
Bank Sta=526.3,551.3
XS Rating Curve= 0 ,0
Exp/Cntr=0.3,0.1

Type RM Length L Ch R = 1 ,26063.2 ,508.4,517.7,527
XS GIS Cut Line= 2
     1933525.986      590360.893     1933481.342      591448.286
#Sta/Elev= 30
       0  948.84      49   947.7    68.6  945.61    78.4  943.58    88.2  940.68
   107.8  932.87   137.3  916.94   147.1  912.76   225.5  887.93   245.1  878.26
   264.7  869.67   303.9  856.29   392.2  831.24   490.2   814.4   519.6  810.03
   558.9  801.95   578.5  796.79   591.5  794.31   598.1  793.81   616.5  795.26
   637.3   797.5   745.2  796.81     755  798.52   774.6  805.39   813.8  812.52
   882.4  828.87   892.2  831.91     902  836.24   931.4  851.28  1088.3  936.18
#Mann= 3 , 0 , 0
       0     .06       0   591.5    .045       0   616.5     .06       0
Bank Sta=591.5,616.5
XS Rating Curve= 0 ,0
Exp/Cntr=0.3,0.1

Type RM Length L Ch R = 1 ,25545.2 ,572.7,575.9,579.1
XS GIS Cut Line= 2
     1933262.907      590265.228     1932893.002      591196.368
#Sta/Elev= 30
       0  949.33    19.6  942.86    39.3  938.38    58.9   936.2   117.9  932.75
   127.7  931.56   137.5   929.2   225.9   896.7   284.9  878.46   294.7  874.71
   363.4  840.29   402.7  824.05   432.2  814.65   491.1  799.25  507.04  793.98
   520.6  791.22   530.4  791.08  534.91   791.2   726.9  794.17   736.7  795.76
     776  807.06   795.6  810.12   834.9  818.38   854.6  823.63   874.2  830.22
   893.9  837.65   913.5  846.35   933.2   856.6   952.8  868.27  1001.9  900.72
#Mann= 3 , 0 , 0
       0      .1       0  507.04    .045       0  534.91     .06       0
Bank Sta=507.04,534.91
XS Rating Curve= 0 ,0
Exp/Cntr=0.3,0.1

Type RM Length L Ch R = 1 ,24968.6 ,400.8,398.8,396.9
XS GIS Cut Line= 2
     1932875.463      590070.709     1932295.095      591154.913
#Sta/Elev= 30
       0  992.56    78.7  982.59   137.7  974.07   167.2  969.27   186.9  963.93
   196.8  959.33   226.3  942.79   295.1  900.23   334.5  877.75     364  863.52
   413.2  842.69   452.6  824.86   501.7  801.01   521.4  789.66   527.1  787.59
   531.3  786.06   541.1  785.49   552.1  786.23   757.5  799.58     787  802.56
   836.2  809.72   875.6  812.74   944.5  815.78     974  818.74  1003.5  824.57
  1052.7  837.16  1141.2  866.65  1180.6  878.77  1200.2   883.9  1229.8  888.98
#Mann= 3 , 0 , 0
       0      .1       0   527.1    .045       0   552.1     .06       0
Bank Sta=527.1,552.1
XS Rating Curve= 0 ,0
Exp/Cntr=0.3,0.1

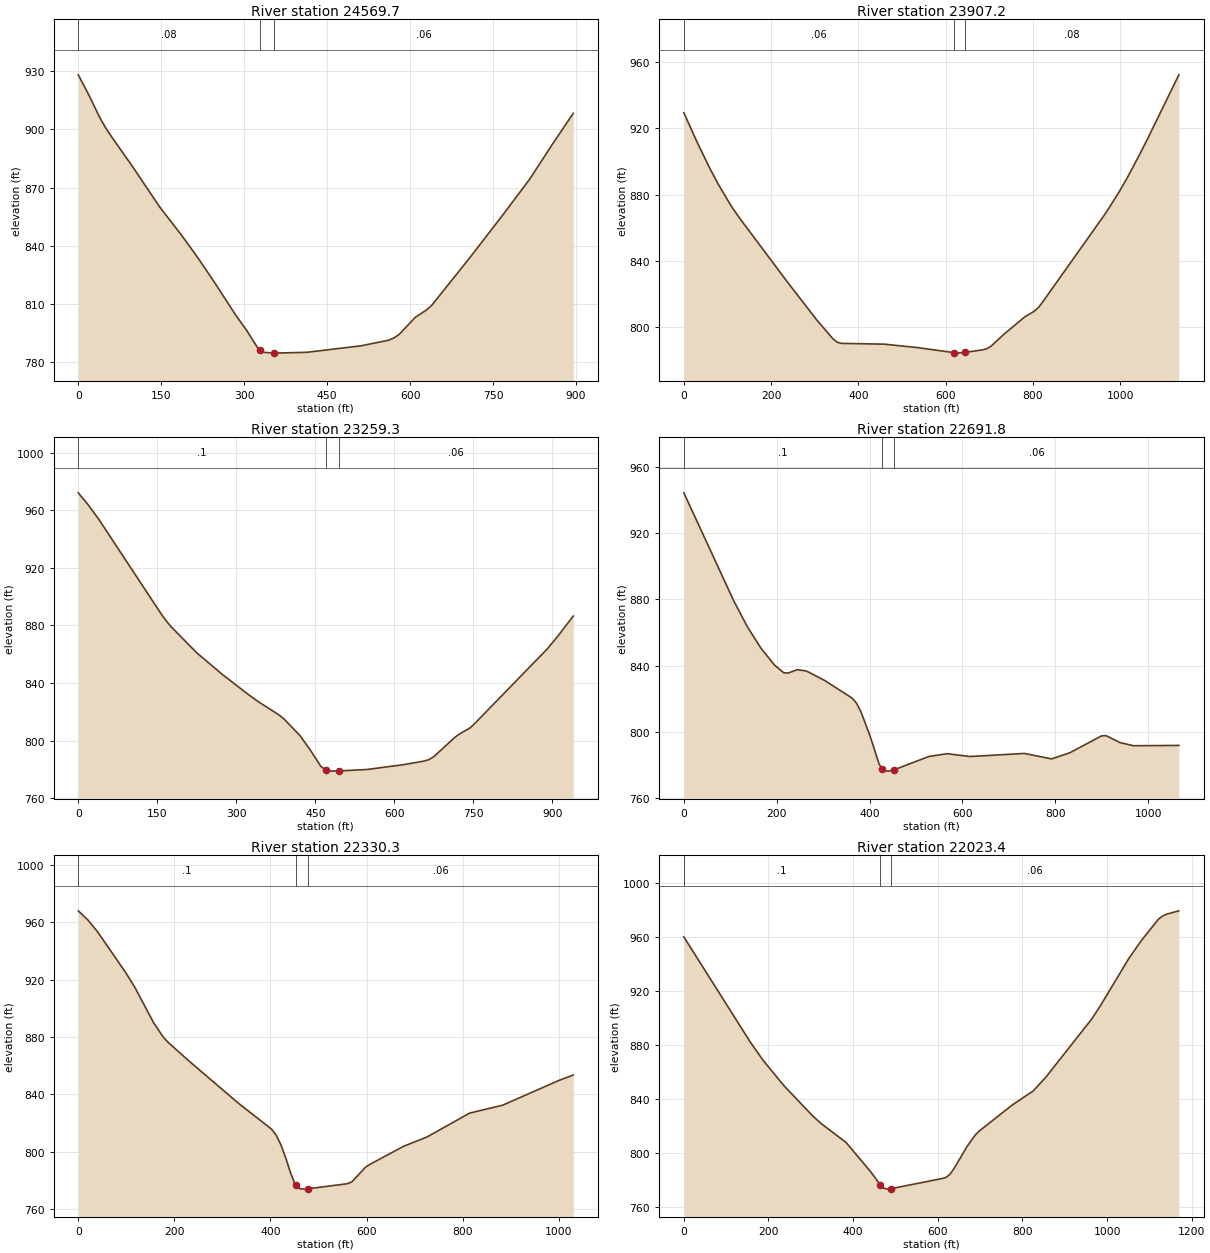
Type RM Length L Ch R = 1 ,24569.7 ,673.4,661.8,650.3
XS GIS Cut Line= 2
     1932440.187      590000.554     1932073.471      590816.897
#Sta/Elev= 30
       0  928.16    19.7   917.4    39.3  905.88    49.2  900.99      59  896.72
    98.3  880.78   147.5  859.91   186.8  845.46   216.4  833.76   245.9  821.33
   285.2  804.05   304.9  796.23   324.5  787.33   329.1  786.31   334.4  785.14
     354   784.7   354.1   784.7     413  785.12   511.4  788.48   560.6  791.34
   570.4  792.48   580.2  794.38   609.7  803.25   629.4  806.92   639.2  809.41
   708.1     834   767.1  855.77   816.2  874.44   855.6  891.71   894.9  908.34
#Mann= 3 , 0 , 0
       0     .08       0   329.1    .045       0   354.1     .06       0
Bank Sta=329.1,354.1
XS Rating Curve= 0 ,0
Exp/Cntr=0.3,0.1

Type RM Length L Ch R = 1 ,23907.2 ,646,647.8,649.5
XS GIS Cut Line= 2
     1931721.082      589695.266     1931711.538      590829.652
#Sta/Elev= 30
       0  929.39    29.3  912.26    58.7   896.2    78.2  886.56   107.6  873.45
   127.1  865.99   234.7  828.12   303.2  804.72   342.3   792.7   352.1  790.75
   361.8  790.12   459.6  789.65   537.9  787.51   619.8   784.5   625.9  784.24
   644.8  784.71   684.6  786.21   694.4  786.87   704.1  788.46   733.5  795.61
   782.4  806.34   801.9  809.33   811.7  811.52   821.5  814.78   968.2   869.3
   997.5  881.55  1017.1  890.54  1046.4  905.09    1066  915.34  1134.4  952.26
#Mann= 3 , 0 , 0
       0     .06       0   619.8    .045       0   644.8     .08       0
Bank Sta=619.8,644.8
XS Rating Curve= 0 ,0
Exp/Cntr=0.3,0.1

Type RM Length L Ch R = 1 ,23259.3 ,562.6,567.2,571.9
XS GIS Cut Line= 2
     1931190.163       589793.28     1931129.575      590730.798
#Sta/Elev= 30
       0  972.05    19.6  963.35    39.1  953.56   156.6  888.34   166.4  883.31
   176.2  879.02   225.1  860.84     274  845.73   322.9   831.9   342.5  826.78
   381.7  817.61   391.4  814.61   420.8   803.4   440.4  793.37     460  782.24
     470  779.35   479.5  778.73     495   778.9     548  779.86   616.5  783.18
   655.7  785.67   665.5  786.72   675.2   788.9   714.4   802.1   724.2  804.68
   743.8  808.81   753.5   812.2   890.5  863.77   910.1  872.43   939.5  886.47
#Mann= 3 , 0 , 0
       0      .1       0     470    .045       0     495     .06       0
Bank Sta=470,495
XS Rating Curve= 0 ,0
Exp/Cntr=0.3,0.1

Type RM Length L Ch R = 1 ,22691.8 ,351.4,361.4,371.3
XS GIS Cut Line= 2
     1930710.243      589783.713     1930474.269      590823.274
#Sta/Elev= 30
       0  944.33   107.6  879.11   136.9  863.49   166.3  850.52   195.6  840.33
   215.2  835.79   224.9  835.64   244.5  837.67   264.1  836.84   303.2  831.15
   361.9   820.6   371.6  817.59   381.4  812.24     401  797.72   420.5   780.7
   427.4   777.9   430.3  776.72   440.1  776.45   452.4  777.21   528.1  785.32
   567.2  786.97   616.1  785.26   733.5  787.11   792.2  783.83   831.3  787.53
   899.8  797.74   909.5  797.85   938.9  793.71   968.2  791.77    1066  791.96
#Mann= 3 , 0 , 0
       0      .1       0   427.4    .045       0   452.4     .06       0
Bank Sta=427.4,452.4
XS Rating Curve= 0 ,0
Exp/Cntr=0.3,0.1

Type RM Length L Ch R = 1 ,22330.3 ,292.7,306.5,320.3
XS GIS Cut Line= 2
     1930536.451      589697.615     1929965.649      590555.412
#Sta/Elev= 30
       0  968.04    19.6   961.8    39.2  953.81    98.1  925.26   117.8  914.59
     157  889.84   176.6  880.04   186.4  876.45   225.7   864.6   333.6  833.69
   402.3  815.67   412.1  811.43     422  804.53   431.8  795.67   441.6  785.37
   451.4  777.15     453  776.65   461.2  774.08     471   773.8     478  774.04
   559.3  777.54   569.2   778.8   598.6  789.31   608.4  791.34   677.1  803.68
   726.2  810.24   814.5  826.85   883.2  832.37  1000.9  849.71  1030.4  853.42
#Mann= 3 , 0 , 0
       0      .1       0     453    .045       0     478     .06       0
Bank Sta=453,478
XS Rating Curve= 0 ,0
Exp/Cntr=0.3,0.1

Type RM Length L Ch R = 1 ,22023.4 ,308.7,311,313.2
XS GIS Cut Line= 2
     1930479.052       589656.16      1929442.68      590198.262
#Sta/Elev= 30
       0  960.34   157.3  882.31   186.7  869.17   235.9  850.34   304.7  827.62
   324.3  822.08   383.3  808.04   442.3  786.04   463.7  776.79   471.8   774.2
   481.6  773.46   488.7  773.74   609.4  781.27   619.2  782.09     629  784.47
   638.8  788.94   668.3  804.57     688  813.41   697.8  816.46   776.4   835.9
   825.6  846.24   855.1   856.3   963.2  899.29   982.8  908.58  1051.6  944.45
  1081.1  957.67  1120.4   973.1  1130.3  975.71  1140.1  977.14  1169.6  979.68
#Mann= 3 , 0 , 0
       0      .1       0   463.7    .045       0   488.7     .06       0
Bank Sta=463.7,488.7
XS Rating Curve= 0 ,0
Exp/Cntr=0.3,0.1

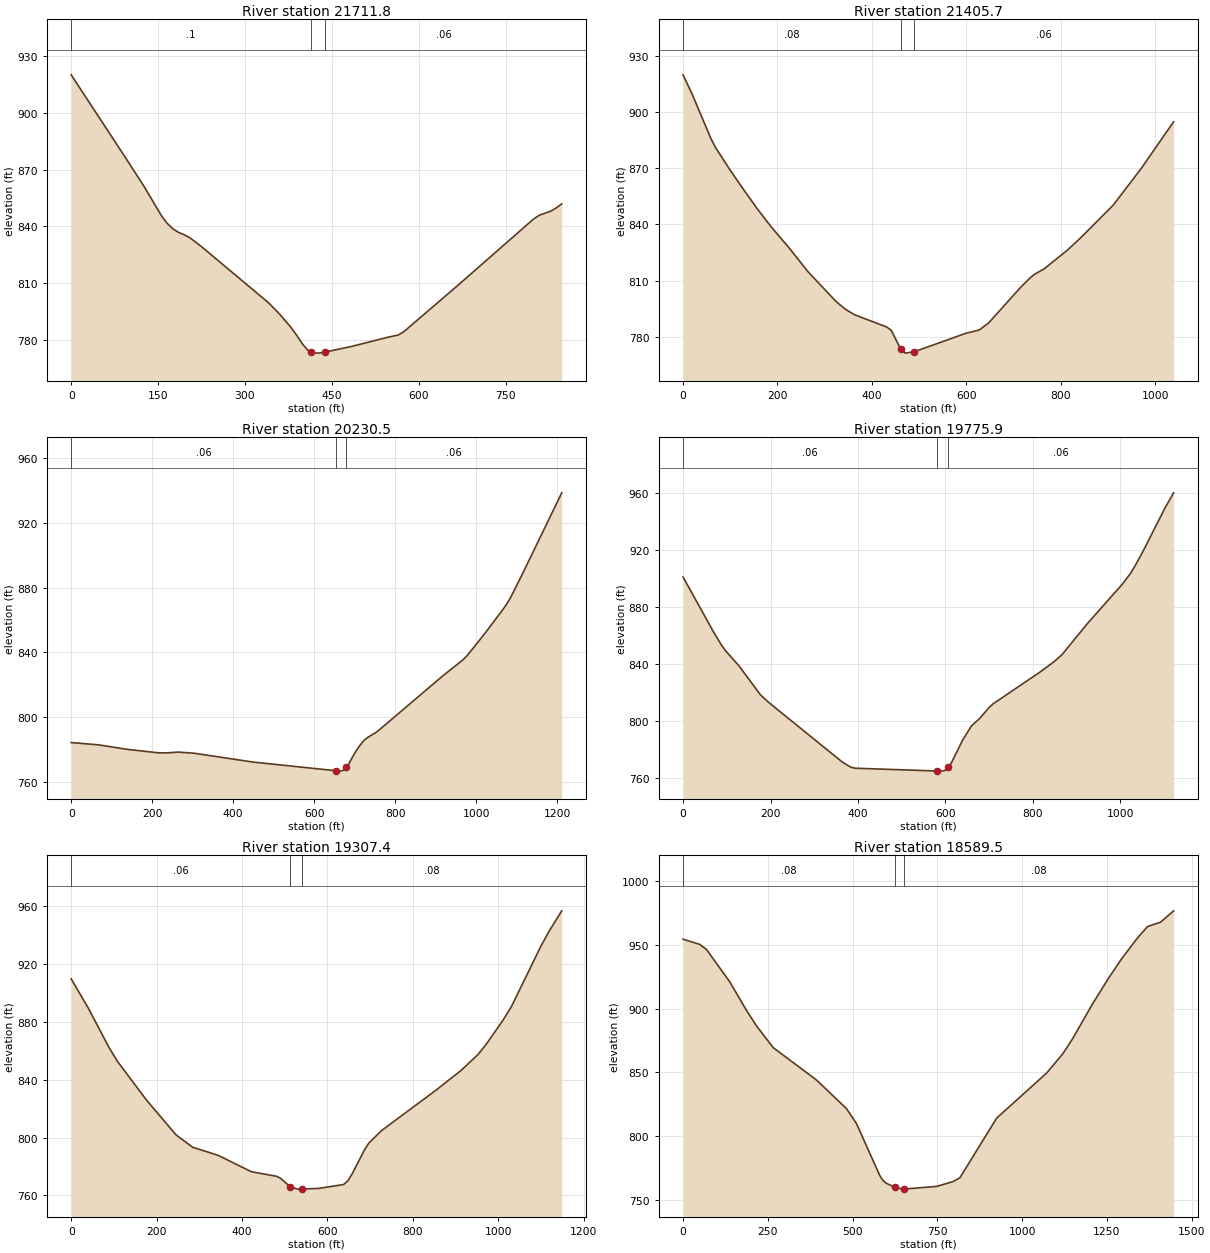
Type RM Length L Ch R = 1 ,21711.8 ,312,306.1,300.2
XS GIS Cut Line= 2
     1930335.555       589436.13     1929556.725      589769.408
#Sta/Elev= 30
       0  920.06    97.4   874.6   126.6  860.72   155.8  845.64   165.5  841.68
   175.3  838.78     185  836.88   194.8  835.62   204.5  834.06     224  829.55
   340.8  799.62   360.3  793.52   379.8   786.5   389.5  782.43   399.2  777.94
     409  774.42   413.6  773.76   418.7  773.02   428.4  773.09   438.6  773.57
   486.9  776.75   545.3  781.31   564.8  782.59   574.5  784.36   671.9  809.94
   798.5   843.9   808.2  845.86   827.7  847.98   837.4  849.69   847.1  851.87
#Mann= 3 , 0 , 0
       0      .1       0   413.6    .045       0   438.6     .06       0
Bank Sta=413.6,438.6
XS Rating Curve= 0 ,0
Exp/Cntr=0.3,0.1

Type RM Length L Ch R = 1 ,21405.7 ,1191.8,1174.4,1156.4
XS GIS Cut Line= 2
     1930204.812      589051.875     1929358.176      589654.565
#Sta/Elev= 30
       0  919.75    19.6  909.23    58.8   885.9    68.6  881.08      98  869.59
   127.4  858.83   156.9  848.42   186.3  838.79   225.5  827.18   264.7  814.74
   323.5  799.02   343.2  794.84   362.8  791.84   431.4  785.25   441.2  783.45
   460.8  773.58   470.6  771.32   490.2   772.1   598.1  781.81   627.5  783.66
   647.1  787.37   715.7  806.58   735.3  811.48   745.1  813.45   764.7  816.23
   813.8  826.15   843.2  833.06   911.8  850.41   970.6  869.81  1039.2  894.73
#Mann= 3 , 0 , 0
       0     .08       0   460.8    .045       0   490.2     .06       0
Bank Sta=460.8,490.2
XS Rating Curve= 0 ,0
Exp/Cntr=0.3,0.1

Type RM Length L Ch R = 1 ,20230.5 ,462.9,454.4,445.9
XS GIS Cut Line= 2
      1929491.31      588460.346     1929060.817      589592.383
#Sta/Elev= 30
       0  784.29    68.4  782.84   136.7  780.14   214.9  777.96   234.4  777.88
   263.7  778.41   302.8  777.71   449.3  772.23   654.6  766.86   664.2  766.64
   673.9  767.26   679.6     769   683.7  770.25   693.5  774.92   703.2  779.05
     713  782.57   722.8  785.58   732.5  787.57   752.1  790.44   761.8   792.4
   918.1  825.61     967  835.33   976.7  837.82   986.5  840.73  1025.6  853.08
  1064.6  866.05  1074.4   869.5  1084.2  873.54  1113.5  888.13  1211.1  938.52
#Mann= 3 , 0 , 0
       0     .06       0   654.6    .045       0   679.6     .06       0
Bank Sta=654.6,679.6
XS Rating Curve= 0 ,0
Exp/Cntr=0.3,0.1

Type RM Length L Ch R = 1 ,19775.9 ,474.9,468.4,462
XS GIS Cut Line= 2
     1928842.806      588418.166     1928779.402      589538.173
#Sta/Elev= 30
       0   900.9    68.9  862.88    88.6  852.87    98.4  848.86   127.9  838.73
   177.1  818.38   196.8  812.88   364.1  771.39   383.8  767.73   393.6  767.06
   580.6   765.1   590.4  765.02   600.3   765.6   606.7  767.65   610.1  768.67
   639.6  786.87   659.3  796.59     679  802.13   698.7   809.2   708.5  812.02
   816.8   834.5   846.3  841.14     866  846.37     925  868.44  1003.7   895.6
  1023.4  903.52  1033.2  908.44  1052.9  919.52  1102.1  949.26  1121.8  959.84
#Mann= 3 , 0 , 0
       0     .06       0   580.6    .045       0   606.7     .06       0
Bank Sta=580.6,606.7
XS Rating Curve= 0 ,0
Exp/Cntr=0.3,0.1

Type RM Length L Ch R = 1 ,19307.4 ,716.2,717.4,718.7
XS GIS Cut Line= 2
     1928268.037      588393.558     1928462.113      589525.418
#Sta/Elev= 30
       0  909.86    39.3  890.02    88.3  862.52     108  852.91   176.7  825.84
   245.4   801.9   284.6  793.29   343.5   787.8     422  776.37   480.9  773.22
   490.8   771.7  512.79  765.93     530  764.34   539.8   764.4   579.1  764.82
     638  767.56   647.8  770.11   657.6  774.84   687.1  791.76   696.9  796.24
   726.3   804.8   853.9   832.8   912.8  846.54   952.1  857.44   971.7  864.63
    1011  881.32  1030.6  890.71  1099.3  932.32  1118.9  942.88  1148.4  956.97
#Mann= 3 , 0 , 0
       0     .06       0  512.79    .045       0   539.8     .08       0
Bank Sta=512.79,539.8
XS Rating Curve= 0 ,0
Exp/Cntr=0.3,0.1

Type RM Length L Ch R = 1 ,18589.5 ,437.8,466,494.1
XS GIS Cut Line= 3
     1927630.269      588393.558      1927757.38      589458.452
     1927904.066      589802.846
#Sta/Elev= 30
       0  954.38    49.2  950.31    68.9   946.4   137.8  920.95   186.9  898.64
   216.5  886.48   265.6  869.46   393.6  844.01   482.1   821.6   511.6  809.83
   580.5  768.98   590.3  765.09   600.2  763.02  624.51  759.99   649.4  758.51
  651.91  758.55   747.8  760.64     797  764.51   816.6  767.46   924.9  814.15
  1072.4  849.51  1120.4  864.72  1149.2   876.5  1206.8  903.25  1254.8  923.76
  1293.2  938.93  1341.2  955.67    1370  964.32  1408.4  967.73  1446.8  976.61
#Mann= 3 , 0 , 0
       0     .08       0  624.51    .045       0  651.91     .08       0
Bank Sta=624.51,651.91
XS Rating Curve= 0 ,0
Exp/Cntr=0.3,0.1