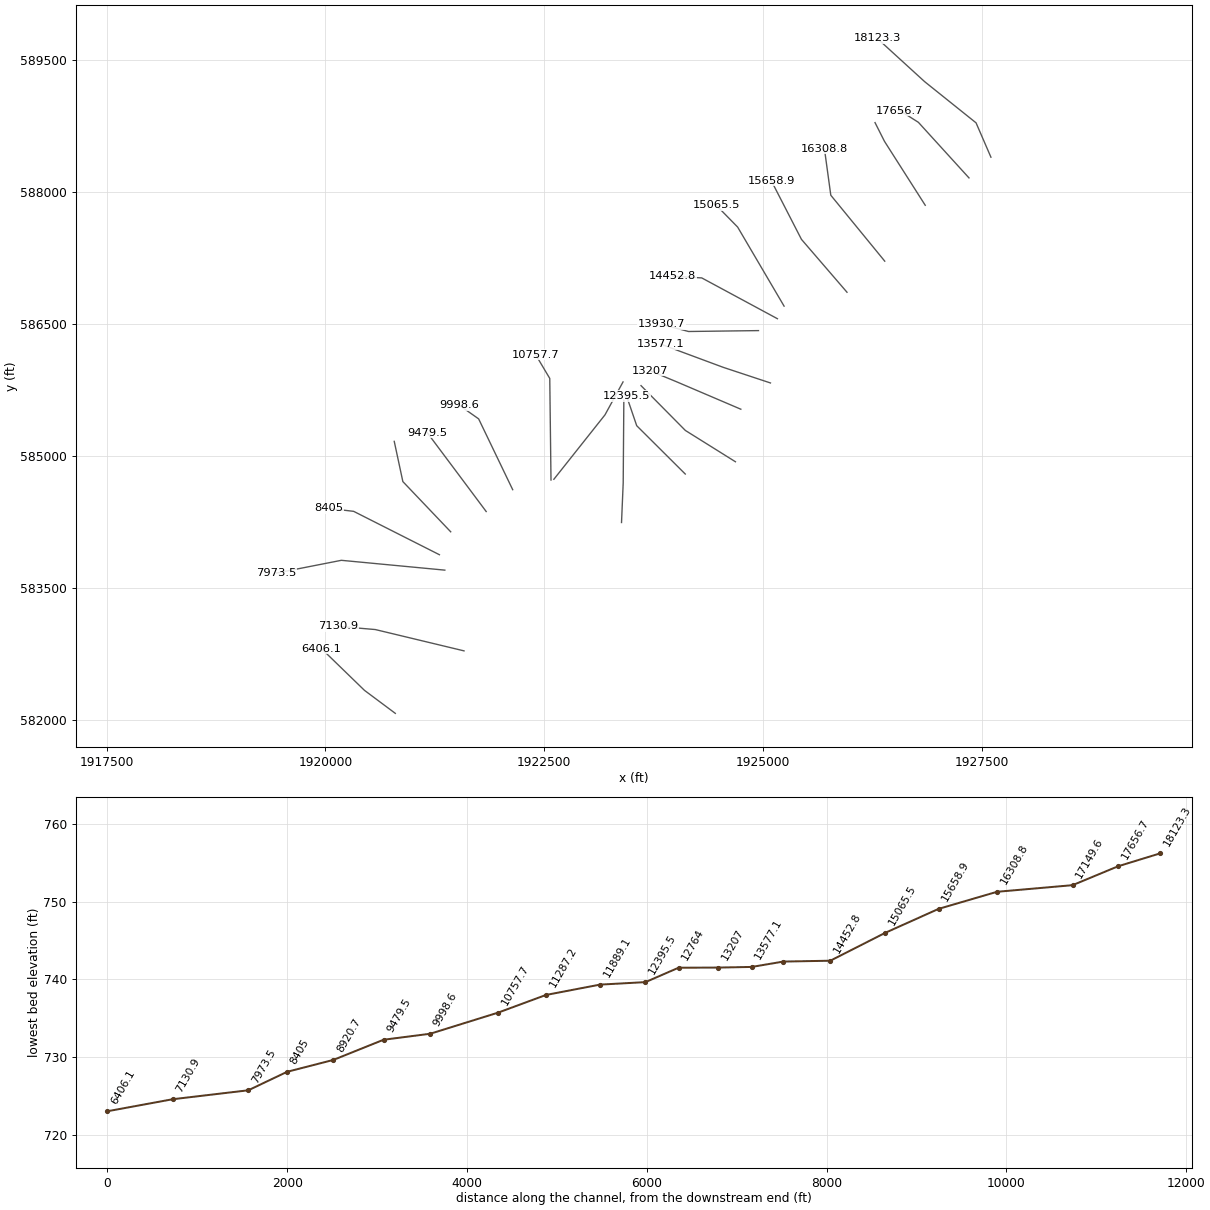
HEC-RAS study MFBgSndyCk.prj: MFBgSndyCk

--- MFBgSndyCk.g01 (geometry) --- (continued)

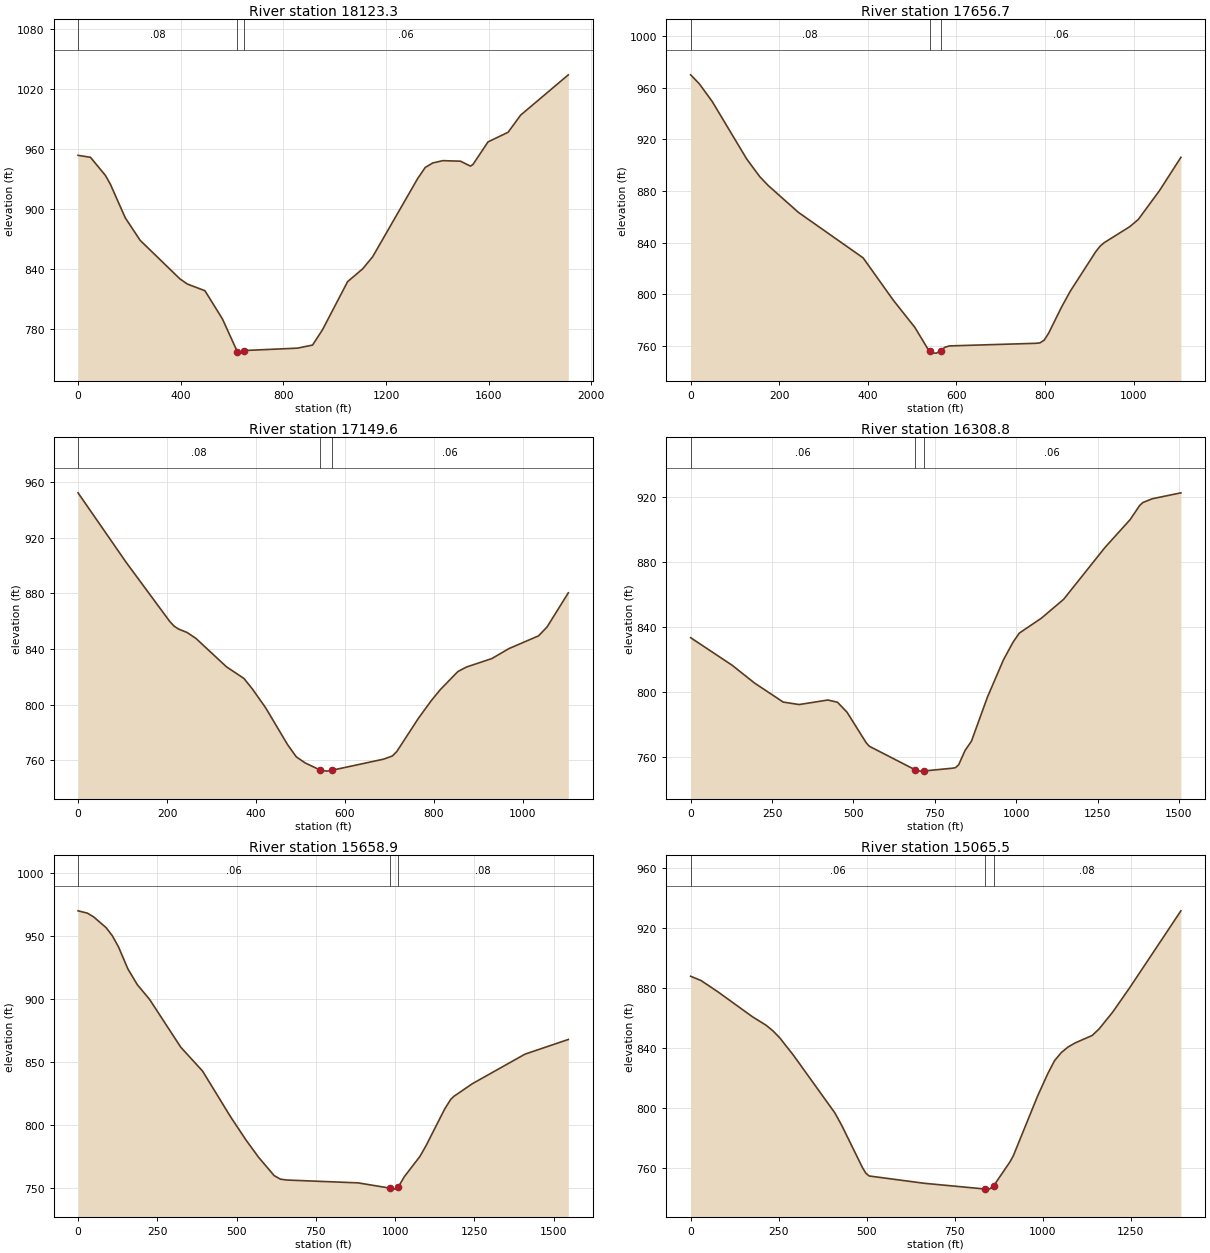
Type RM Length L Ch R = 1 ,18123.3 ,470.6,466.4,462.2
XS GIS Cut Line= 4
     1927602.755      588398.665     1927432.775      588789.353
     1926845.837      589257.463     1926303.009      589750.479
#Sta/Elev= 30
       0  953.63    48.4  951.62   106.5   933.6   125.9  924.81     184  891.22
   242.1  868.73     397  830.27   426.1  825.13   494.3  818.49   562.6   790.3
   621.1  757.33   630.8  756.19   647.2  758.76   855.1  761.17   913.6  764.23
   952.6   779.6  1050.1  827.51  1108.6  840.23  1147.6  852.29  1323.5  930.55
  1352.8  941.54  1382.1  945.99  1421.2  948.29  1489.7  947.76  1528.8  942.85
  1538.6  944.46  1597.2     967  1675.5  976.62  1724.3  993.73  1910.1 1033.95
#Mann= 3 , 0 , 0
       0     .08       0   621.1    .045       0   647.2     .06       0
Bank Sta=621.1,647.2
XS Rating Curve= 0 ,0
Exp/Cntr=0.3,0.1

Type RM Length L Ch R = 1 ,17656.7 ,511.5,506.8,502.1
XS GIS Cut Line= 3
     1927352.128      588163.139      1926773.92      588795.355
       1926562.5      588928.813
#Sta/Elev= 30
       0  969.92    19.5  963.03    48.7  949.28   126.6  904.78   155.8  891.21
   175.2  884.22   243.4  863.45   389.4  828.27   457.6  795.47   506.3  774.41
   535.5   757.8   539.3  756.54   545.2  754.59   554.9  754.54   564.3  756.48
   574.4  759.16   584.2  760.12   778.9  762.14   788.6  762.47   798.3  764.62
   808.1  769.91   837.3  790.13   856.8  802.32   914.4  832.98   924.1  837.22
   933.7  840.04   991.4  852.42  1010.6  857.98  1058.7  880.42  1106.8  906.07
#Mann= 3 , 0 , 0
       0     .08       0   539.3    .045       0   564.3     .06       0
Bank Sta=539.3,564.3
XS Rating Curve= 0 ,0
Exp/Cntr=0.3,0.1

Type RM Length L Ch R = 1 ,17149.6 ,837.5,840.7,843.9
XS GIS Cut Line= 3
     1926852.045      587852.126      1926386.33      588579.321
     1926278.465      588792.145
#Sta/Elev= 30
       0  952.32   107.9  902.42   206.1  859.81   215.9  856.45   225.7  854.35
   245.3  851.82     265   847.6   333.6  827.16   372.9   818.8   392.5  810.96
     422  797.53     471  771.18   490.6  762.39   510.3  758.07   544.9  752.76
   559.3  752.11   569.9  752.67   686.9  760.73   706.5     763   716.4  766.15
   765.4  790.25   794.8  803.13   814.5  810.79   853.7   823.7   873.1     827
   930.4  833.11   968.5  840.24  1035.3  849.44  1054.4  855.85  1102.1  880.38
#Mann= 3 , 0 , 0
       0     .08       0   544.9    .045       0   569.9     .06       0
Bank Sta=544.9,569.9
XS Rating Curve= 0 ,0
Exp/Cntr=0.3,0.1

Type RM Length L Ch R = 1 ,16308.8 ,653.5,649.1,644.1
XS GIS Cut Line= 3
     1926389.507      587216.403     1925773.175      587966.167
     1925700.105       588496.72
#Sta/Elev= 30
       0  833.53   127.4  816.55   196.1  805.59   284.3  793.84   333.3  792.31
   421.6   795.1     451  793.75   480.4  787.61   539.2  768.76     549  766.58
   690.4  752.01   705.9  751.26   715.4  751.34   803.9  753.05   813.7  753.41
   823.5  755.22   843.1  764.04   862.7  769.74   911.8  796.91   960.8  819.81
     990  830.59  1009.5  836.32  1077.7  845.59  1145.8  857.18  1272.4  889.05
  1350.3  906.36  1379.6  915.07  1389.3  916.86  1418.5   919.2  1506.1  922.84
#Mann= 3 , 0 , 0
       0     .06       0   690.4    .045       0   715.4     .06       0
Bank Sta=690.4,715.4
XS Rating Curve= 0 ,0
Exp/Cntr=0.3,0.1

Type RM Length L Ch R = 1 ,15658.9 ,591.1,592.8,594.5
XS GIS Cut Line= 3
     1925958.228      586862.901     1925437.906      587464.242
     1925093.304      588131.369
#Sta/Elev= 30
       0  969.99    29.4  968.16    49.1  965.19    88.4  956.68     108  950.24
   127.6  941.33   157.1  923.91   186.5  911.52   225.8  899.61     324  861.72
   392.7  842.78     481  806.48   530.1  787.91   569.4  774.33   618.5   759.8
   638.1  757.01   657.8   756.3     883  754.04   984.2  749.84    1000  749.07
  1009.2  750.47  1029.2  759.04    1078     775  1097.5  783.58    1156  812.57
  1175.5  820.38  1185.3  822.74  1243.8   832.8  1409.6  856.24  1546.1  867.86
#Mann= 3 , 0 , 0
       0     .06       0   984.2    .045       0  1009.2     .08       0
Bank Sta=984.2,1009.2
XS Rating Curve= 0 ,0
Exp/Cntr=0.3,0.1

Type RM Length L Ch R = 1 ,15065.5 ,597.6,612.7,627.7
XS GIS Cut Line= 3
     1925239.445      586704.911     1924708.891      587603.993
      1924463.92      587852.661
#Sta/Elev= 30
       0  887.78    29.3  884.96      78  877.32   175.6   860.8   214.6  855.12
   234.2  851.34   253.7  846.61   292.7  834.98   409.8  796.76   429.3  788.46
   487.8  760.53   497.6  756.66   507.3  754.75   663.4   749.9   835.9  746.08
   848.8     746   860.9  748.16   907.4   764.2   917.1  768.34   985.4  807.76
  1014.7  822.88  1034.2  831.64  1053.6  837.06    1073  840.75  1092.4  843.36
  1140.9  848.34  1160.3  852.62  1199.1  863.87  1247.6  880.17    1393  931.35
#Mann= 3 , 0 , 0
       0     .06       0   835.9    .045       0   860.9     .08       0
Bank Sta=835.9,860.9
XS Rating Curve= 0 ,0
Exp/Cntr=0.3,0.1

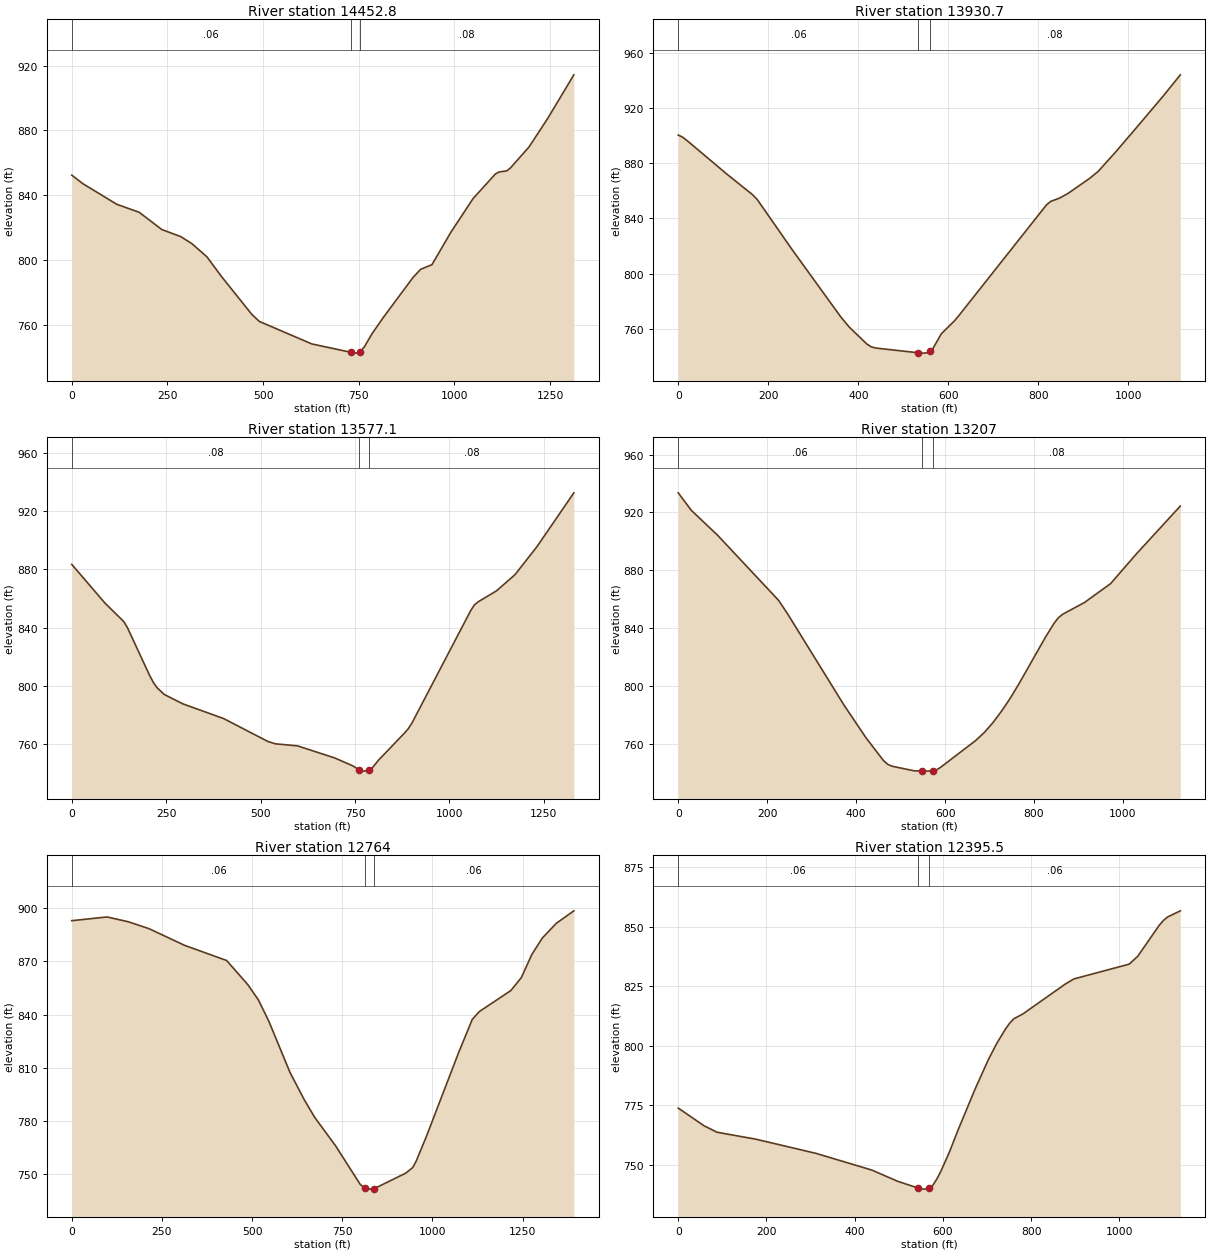
Type RM Length L Ch R = 1 ,14452.8 ,508,522,535.9
XS GIS Cut Line= 3
     1925163.198      586561.948     1924299.063      587025.785
     1923968.061      587045.623
#Sta/Elev= 30
       0  852.35    29.4  847.01   117.7  834.35   176.5  829.37   235.4  818.74
   284.4  814.43   313.8  810.06   353.1  801.94   392.3  789.46   470.8   766.3
   490.4  761.97   627.7  748.08   729.4  742.93   745.4  742.41   754.4  743.28
     765  746.34   784.6  754.29     814  764.31   892.5   789.3   912.1   794.2
   941.5  797.04   990.5  816.89    1049  837.88  1107.5  853.11  1117.3  854.34
  1136.8  854.94  1146.6  856.78  1195.3  869.76  1244.1  887.38  1312.4  914.31
#Mann= 3 , 0 , 0
       0     .06       0   729.4    .045       0   754.4     .08       0
Bank Sta=729.4,754.4
XS Rating Curve= 0 ,0
Exp/Cntr=0.3,0.1

Type RM Length L Ch R = 1 ,13930.7 ,363.7,353.5,343.3
XS GIS Cut Line= 3
     1924946.988      586426.802     1924148.059      586416.479
     1923841.931      586497.263
#Sta/Elev= 30
       0  900.42     9.7  898.88    19.5  896.42   107.2  872.32   165.6  857.04
   175.4  853.74   253.3  817.25   360.5  768.86     380  761.18     419  748.94
   428.7  746.88   438.5     746   533.7  742.54   545.7   742.3   555.4  742.64
   558.7   743.5   565.1  745.16   584.6  756.34   613.9  765.76   623.6  769.54
   818.2  849.75   827.8  852.34     847  854.65   866.2  858.11   914.1  868.98
   933.3  874.12   971.7  888.05  1019.7  906.36  1077.2  928.52  1115.6  944.06
#Mann= 3 , 0 , 0
       0     .06       0   533.7    .045       0   558.7     .08       0
Bank Sta=533.7,558.7
XS Rating Curve= 0 ,0
Exp/Cntr=0.3,0.1

Type RM Length L Ch R = 1 ,13577.1 ,371.7,369.9,368.1
XS GIS Cut Line= 3
     1925083.773      585831.245     1924543.689      586009.156
     1923829.996      586272.883
#Sta/Elev= 30
       0  883.44    88.2   856.8   137.3  844.32   147.1  840.22   205.9  807.42
   215.7  802.62   225.5  798.92   245.1  794.17   294.1  787.76     402  777.69
   519.6  761.92   539.2  760.35   597.9  758.93   695.4  750.74   744.2  745.22
   761.9  742.32   773.5  741.61   786.9  742.19     793  742.95   812.5  749.18
   880.8  767.66   890.5  770.49   900.3  774.34  1056.4  851.74  1066.1   855.6
  1075.9  857.72  1124.6  865.27  1173.4   876.3    1232  895.64  1329.5  932.52
#Mann= 3 , 0 , 0
       0     .08       0   761.9    .045       0   786.9     .08       0
Bank Sta=761.9,786.9
XS Rating Curve= 0 ,0
Exp/Cntr=0.3,0.1

Type RM Length L Ch R = 1 ,13207   ,453,442.9,432.7
XS GIS Cut Line= 3
     1924745.311      585532.699     1924013.136      585843.953
      1923704.97      585971.032
#Sta/Elev= 30
       0  933.56    29.5  921.45    88.4  904.34   225.9  859.28   245.6   850.2
   373.2  786.85   422.4  764.47   461.6  748.78   471.5  746.12   481.3  744.88
   530.4  741.74   547.7   741.6  559.88  741.53   572.7  741.79   579.5  742.21
   589.3  744.03   667.9  762.43   687.5  767.96   707.2  774.83   726.8  782.85
   746.5  791.81   766.1  801.78     825   833.6   844.6  843.33   854.4  847.26
   864.2  849.74   913.2  857.84   972.1  870.88  1030.9  891.68  1128.9  924.42
#Mann= 3 , 0 , 0
       0     .06       0   547.7    .045       0   572.7     .08       0
Bank Sta=547.7,572.7
XS Rating Curve= 0 ,0
Exp/Cntr=0.3,0.1

Type RM Length L Ch R = 1 ,12764   ,368,368.5,369
XS GIS Cut Line= 3
     1924683.476      584935.341     1924111.622      585291.161
     1923604.846      585800.933
#Sta/Elev= 30
       0  892.99    97.6  895.09   156.2  892.41   214.7  888.44   312.4  879.11
   429.5  870.51   488.1  856.93   517.3  848.39   546.6  836.21   605.2  807.37
   644.2  792.16   673.5  782.05   731.8  765.89   799.8  744.21   813.4  741.91
   819.2  741.51   838.4  741.75   926.1  750.52   945.5  753.68   955.2  757.35
   984.4  771.74  1071.8  818.03  1110.6  837.29  1130.1  841.68  1217.5  853.55
  1246.6  860.84  1275.8   873.9  1304.9  883.19  1343.8  891.53  1392.3  898.55
#Mann= 3 , 0 , 0
       0     .06       0   813.4    .045       0   838.4     .06       0
Bank Sta=813.4,838.4
XS Rating Curve= 0 ,0
Exp/Cntr=0.3,0.1

Type RM Length L Ch R = 1 ,12395.5 ,528.1,506.1,484
XS GIS Cut Line= 3
     1924110.302      584795.625     1923555.653       585345.17
     1923439.708      585683.093
#Sta/Elev= 30
       0  773.73    58.6  766.28    87.8  763.58   175.7  760.66   312.3  754.69
   439.2  747.65   497.8  742.92     543  740.16   556.3  739.66     568  739.95
   575.8  740.91   585.6  743.74   595.4   747.2   614.9  755.36   634.4  764.58
   673.4  781.96   702.7     794   722.2  800.99   741.8  806.98   751.5  809.47
   761.3  811.35   780.8  813.25   877.4  825.87   896.7  828.01  1022.2  834.23
  1041.5  837.53  1089.8  850.45  1099.4  852.54  1109.1  854.04    1138  856.64
#Mann= 3 , 0 , 0
       0     .06       0     543    .045       0     568     .06       0
Bank Sta=543,568
XS Rating Curve= 0 ,0
Exp/Cntr=0.3,0.1

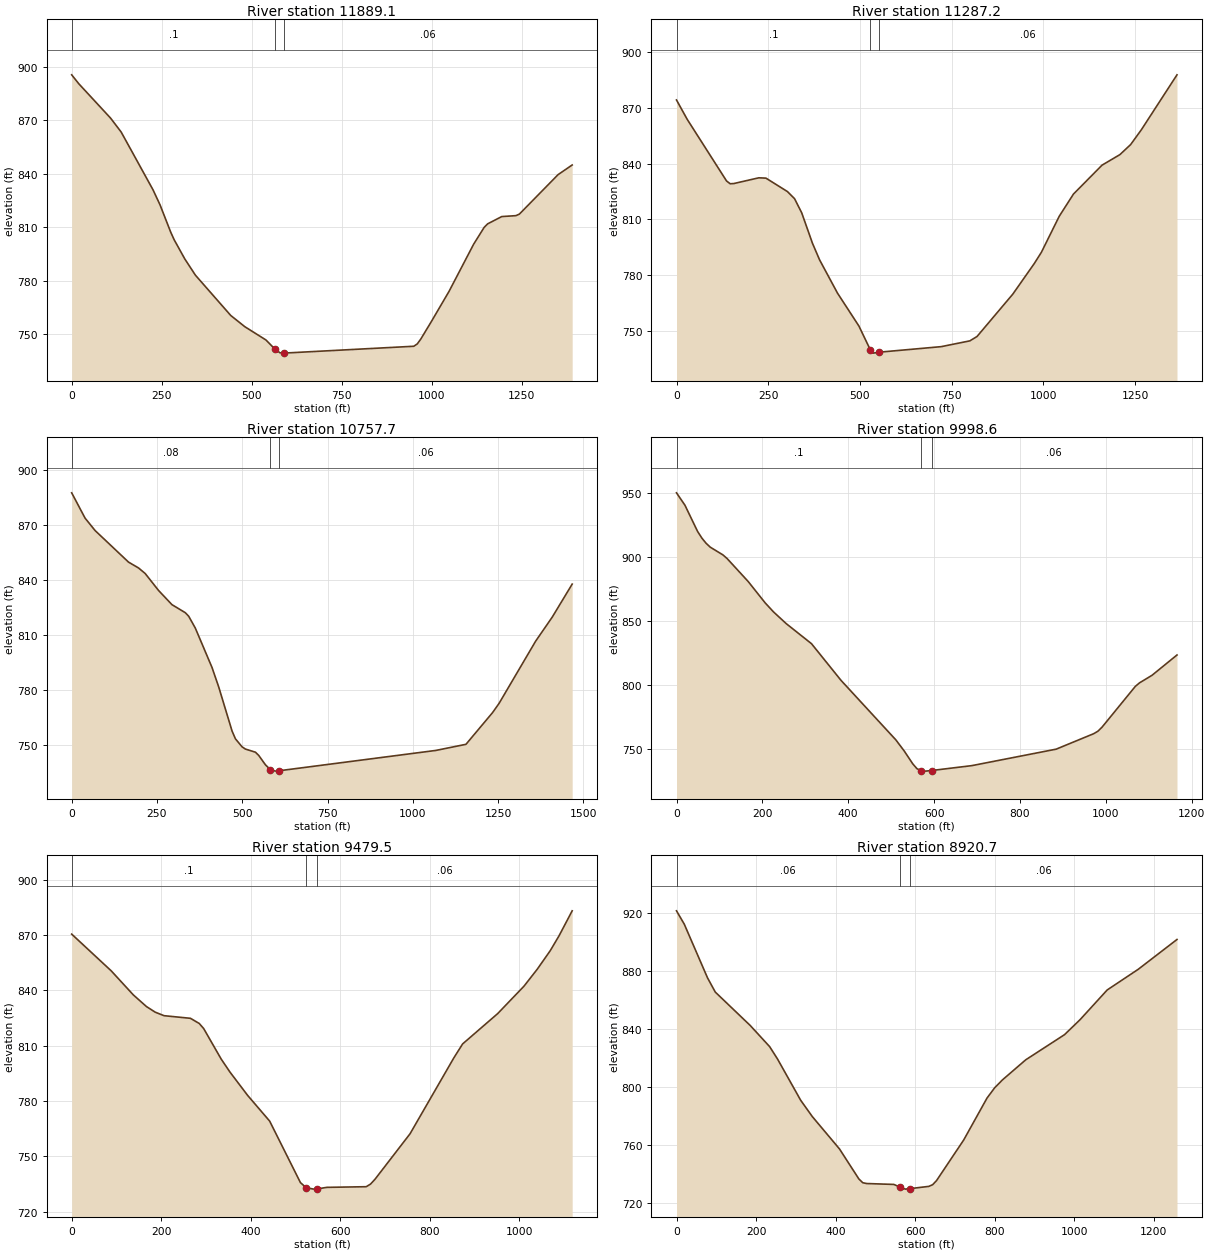
Type RM Length L Ch R = 1 ,11889.1 ,619.5,601.6,583.8
XS GIS Cut Line= 3
     1923382.123      584244.186     1923401.328      584695.492
     1923408.529      585634.112
#Sta/Elev= 30
       0  895.63    19.6  890.65     108  871.33   137.5  863.49   225.9  831.07
   245.5  822.58     275  807.32   284.8  802.97   314.2  792.25   343.7  783.12
   441.9  760.48     481  754.18   539.7  746.72   565.3  741.45   578.8  739.52
   588.6  739.34   590.3  739.36   950.4   743.2   960.2  744.55   969.9  747.26
   999.3  757.11  1048.2  773.98  1116.6  800.49  1145.9  809.97  1155.7  811.96
  1194.8  816.03  1233.9  816.54  1243.7  817.41  1351.2  839.57  1390.4     845
#Mann= 3 , 0 , 0
       0      .1       0   565.3    .045       0   590.3     .06       0
Bank Sta=565.3,590.3
XS Rating Curve= 0 ,0
Exp/Cntr=0.3,0.1

Type RM Length L Ch R = 1 ,11287.2 ,511.8,529.8,547.8
XS GIS Cut Line= 3
      1922609.26      584736.129     1923192.845      585468.081
     1923399.348      585842.963
#Sta/Elev= 30
       0  874.21    29.2  863.79   136.5  830.61   146.3  829.14     156  829.24
   224.3  832.33   243.8  832.16   302.3  824.94   321.8   821.1   341.3  813.48
   370.6  797.11     390  788.19   438.8  770.29   497.3  752.55   528.2  739.81
   536.3  738.01   553.2  738.53   721.6   741.5   799.6  744.61   819.1  746.96
   916.6  769.75     975  786.18   994.5  792.25  1043.1  811.62    1082  823.61
  1159.8  839.14  1208.5  844.81  1237.7   850.2  1266.8  858.13  1364.1  887.74
#Mann= 3 , 0 , 0
       0      .1       0   528.2    .045       0   553.2     .06       0
Bank Sta=528.2,553.2
XS Rating Curve= 0 ,0
Exp/Cntr=0.3,0.1

Type RM Length L Ch R = 1 ,10757.7 ,743.1,757.5,771.5
XS GIS Cut Line= 3
     1922576.347        584727.4     1922562.274      585882.888
     1922402.693      586150.233
#Sta/Elev= 30
       0  887.67    39.2  873.87    68.6  867.08   166.5  849.86   195.9  846.66
   215.4  843.63   254.6  834.37   293.8  826.64     333  822.23   342.8  820.34
   362.3  813.86   411.3  792.33   430.9   781.7   470.1   757.6   479.9  753.39
   499.4     749   509.2  747.79   538.6  746.08   548.4  744.27     568  739.18
   582.5  736.53   597.4  735.75   607.5  735.94  1067.4  747.05  1155.6  750.39
  1233.4  767.66  1252.9  772.82  1359.9  806.72  1408.6  819.86  1466.9  837.84
#Mann= 3 , 0 , 0
       0     .08       0   582.5    .045       0   607.5     .06       0
Bank Sta=582.5,607.5
XS Rating Curve= 0 ,0
Exp/Cntr=0.3,0.1

Type RM Length L Ch R = 1 ,9998.6  ,513.9,519.1,524.3
XS GIS Cut Line= 3
     1922138.726      584617.644      1921749.74      585422.862
     1921527.437       585578.81
#Sta/Elev= 30
       0  949.87    19.6  940.26    49.1  919.81      59  914.65    68.8  910.62
    78.6  907.54   108.1  901.52   117.9  898.67   167.1  880.73   206.4  864.17
     226  857.08   255.5  847.98   314.5  832.31   383.2  803.76     511  757.36
   530.6  748.65   550.3  738.72   560.1  734.94   569.2   733.5   579.8  733.03
   594.2   733.5   687.9  737.31   884.4  750.15   971.8   762.2   981.5   764.1
   991.2  767.28  1068.8  799.08  1078.5   801.8  1107.6  807.69  1165.8  823.52
#Mann= 3 , 0 , 0
       0      .1       0   569.2    .045       0   594.2     .06       0
Bank Sta=569.2,594.2
XS Rating Curve= 0 ,0
Exp/Cntr=0.3,0.1

Type RM Length L Ch R = 1 ,9479.5  ,554.9,558.2,561.5
XS GIS Cut Line= 3
     1921835.812      584369.243     1921511.546      584801.576
     1921164.467      585263.247
#Sta/Elev= 30
       0  870.51    88.4  850.58   137.6  837.58     167  831.24   186.7  828.18
   206.3  826.29   265.3  824.87     285  822.06   294.8  819.33   334.1  802.71
   353.7  795.68     393  783.09   442.2  769.15     511  735.79   523.6  733.07
   540.4  732.26   548.6  732.38   569.8  733.22   657.9  733.57   667.7  735.02
   677.5   737.6   755.8  762.26   853.7  803.44   873.3  810.99   951.6  827.42
  1010.3  842.28  1039.7  851.39  1069.1  861.57  1088.6  869.57    1118  883.14
#Mann= 3 , 0 , 0
       0      .1       0   523.6    .045       0   548.6     .06       0
Bank Sta=523.6,548.6
XS Rating Curve= 0 ,0
Exp/Cntr=0.3,0.1

Type RM Length L Ch R = 1 ,8920.7  ,505.8,515.3,524.9
XS GIS Cut Line= 3
     1921430.449      584138.601     1920883.824      584709.776
     1920785.338       585167.26
#Sta/Elev= 30
       0  921.18    19.5  912.03    78.1     875    97.6  865.25   185.4  842.28
   234.2  827.74   253.8  819.33   312.3  790.82   341.6  779.57   409.9  757.32
   458.7  736.63   468.5  734.07   478.3  733.52   546.6   732.9   562.1  731.04
   575.9  729.67   587.1     730   634.4  731.56   644.2  732.72     654  735.57
   722.3  763.51   780.8   792.3   800.3  799.47   819.8  804.87   878.3  818.67
   975.8  835.97  1014.8  846.26  1083.1  866.73  1161.1  880.94  1258.6  901.46
#Mann= 3 , 0 , 0
       0     .06       0   562.1    .045       0   587.1     .06       0
Bank Sta=562.1,587.1
XS Rating Curve= 0 ,0
Exp/Cntr=0.3,0.1

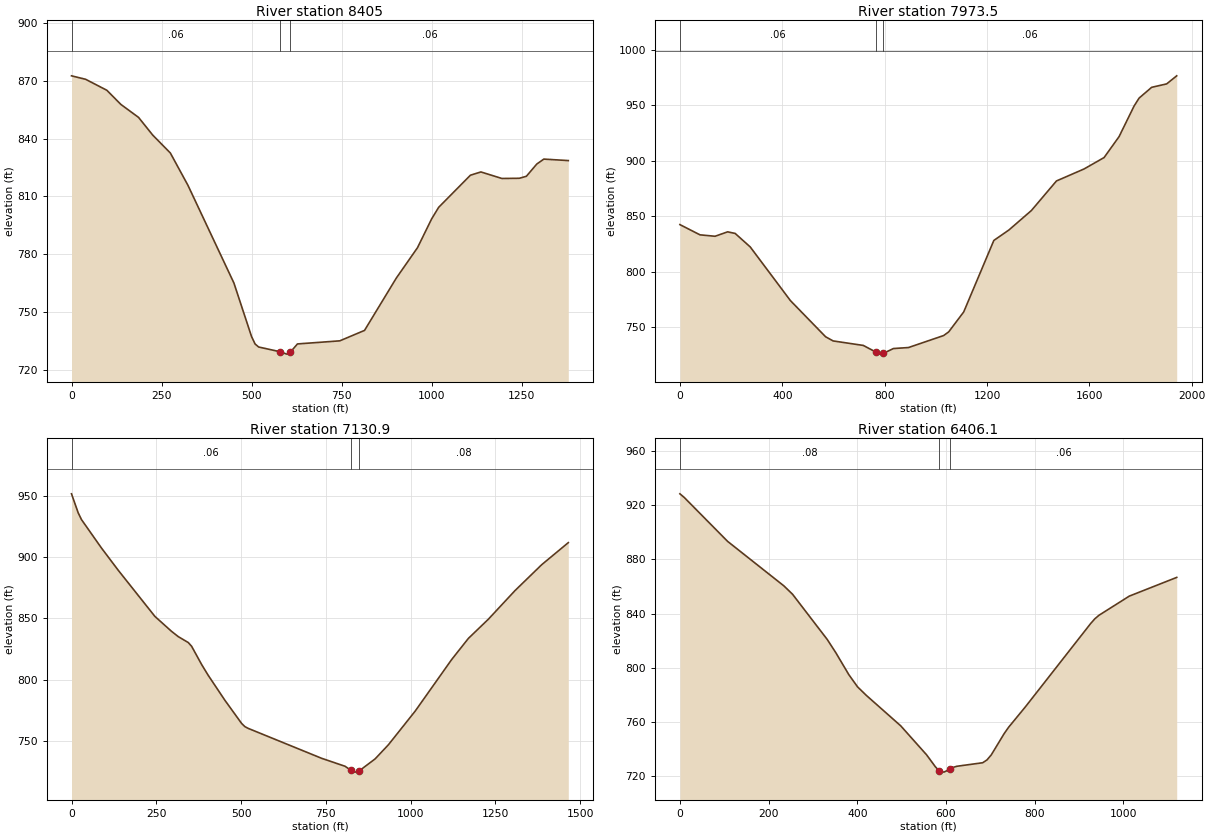
Type RM Length L Ch R = 1 ,8405    ,421.1,431.3,441.4
XS GIS Cut Line= 3
      1921301.58      583877.987     1920321.404      584371.416
     1920041.989      584404.145
#Sta/Elev= 30
       0  872.65    39.2  870.85      98  865.16   137.2  857.78   186.2  851.04
   225.4  841.88   274.3  832.58   323.3  815.75   450.7  765.08   499.7  737.25
   509.5  733.41   519.3  731.84   578.1  729.41   597.7  728.14   607.5  729.22
   627.1  733.43   744.6  735.04   813.2  740.46   901.4  767.63   960.2  783.41
   999.4  798.35    1019  804.38  1107.1  821.05  1136.2  822.74  1194.4  819.35
  1242.9  819.45  1262.3  820.48  1291.4  826.87  1310.8  829.41  1378.7  828.64
#Mann= 3 , 0 , 0
       0     .06       0   578.1    .045       0   607.5     .06       0
Bank Sta=578.1,607.5
XS Rating Curve= 0 ,0
Exp/Cntr=0.3,0.1

Type RM Length L Ch R = 1 ,7973.5  ,845.8,842.2,838.5
XS GIS Cut Line= 3
     1921363.546      583702.678     1920181.146      583814.388
     1919441.336      583669.827
#Sta/Elev= 30
       0  842.46    78.5  833.23   137.4  831.95   186.5  835.94   215.9   834.5
   274.8  822.34   431.9  773.97   569.3  741.42   598.7  737.66   716.5  733.61
   765.6  727.67   785.2  725.77     795  726.44   834.3   730.8   893.2   731.7
  1030.6   742.5  1050.2  745.76  1109.1  763.77  1226.8  828.18  1285.6  837.57
  1373.7  855.17  1471.6  881.78  1579.2  892.56  1657.6  902.84  1716.3  921.74
    1775  949.32  1794.6  956.45  1843.6  966.13  1902.3  969.23  1941.5  976.49
#Mann= 3 , 0 , 0
       0     .06       0   765.6    .045       0     795     .06       0
Bank Sta=765.6,795
XS Rating Curve= 0 ,0
Exp/Cntr=0.3,0.1

Type RM Length L Ch R = 1 ,7130.9  ,739.7,724.4,709
XS GIS Cut Line= 3
     1921582.756      582784.535     1920568.662        583027.1
     1920147.961       583062.99
#Sta/Elev= 30
       0  951.42    19.7  935.94    29.5  930.39    88.5  907.21   137.7  889.17
   245.9  851.53   295.1  839.32   314.8  835.05   344.3  830.21   354.1  827.22
   383.6  812.36   403.3  803.43   452.5   783.1   501.7  764.27   511.5  761.65
   521.4  760.23   737.8  735.86   806.6   729.4     823   726.3   836.1  724.62
     848  725.58   895.2  735.39   934.5  746.93  1013.2  774.27  1121.2  816.46
  1170.4  833.63  1229.3  849.27  1307.8  872.57  1386.4  893.65  1464.9  911.63
#Mann= 3 , 0 , 0
       0     .06       0     823    .045       0     848     .08       0
Bank Sta=823,848
XS Rating Curve= 0 ,0
Exp/Cntr=0.3,0.1

Type RM Length L Ch R = 1 ,6406.1  ,541.9,560.3,578.6
XS GIS Cut Line= 3
     1920797.709      582073.747     1920444.795      582335.904
     1919955.094      582808.758
#Sta/Elev= 30
       0  928.35     9.8  925.66   107.5   893.3   234.5  860.45     254  854.29
   332.2  820.95   351.7  811.12     381  794.95   400.6  785.99   420.1  779.78
     498  757.22   556.3  735.85   575.8  727.17   583.9  724.22   585.5  723.64
   595.2  723.08   608.9  725.14   614.7  726.44   624.4  727.39   682.8     730
   692.5  732.07   702.2  735.81   731.4  751.56   741.1  756.09     780  771.58
   925.9  832.51   935.6  836.12   945.3  838.82  1013.4  852.89  1120.4   866.7
#Mann= 3 , 0 , 0
       0     .08       0   583.9    .045       0   608.9     .06       0
Bank Sta=583.9,608.9
XS Rating Curve= 0 ,0
Exp/Cntr=0.3,0.1