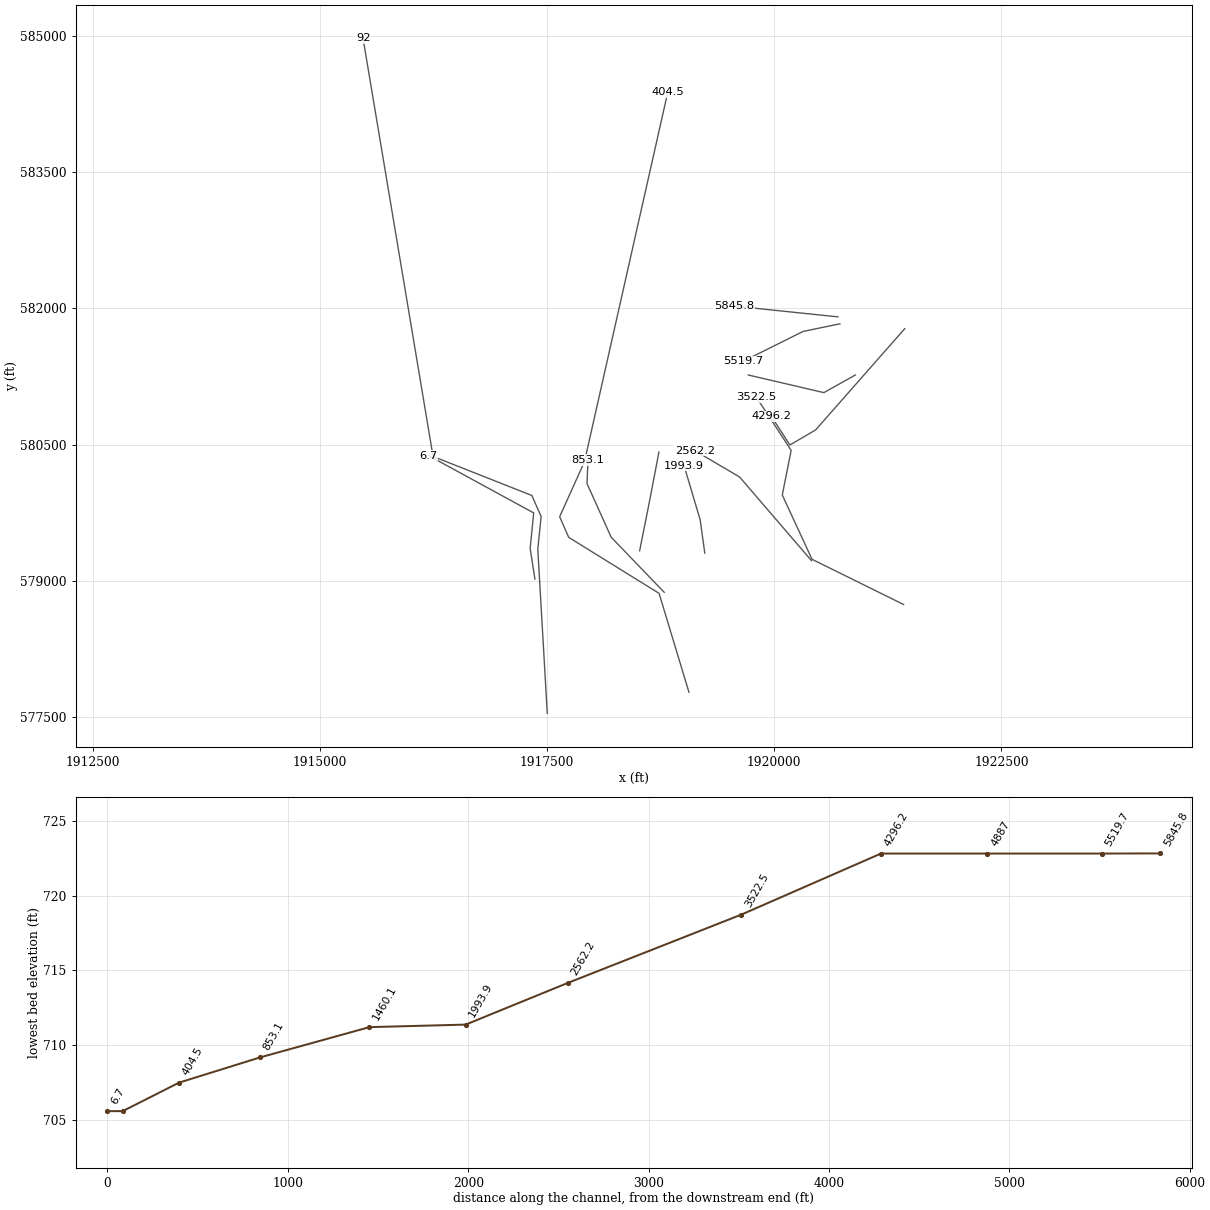
HEC-RAS study MFBgSndyCk.prj: MFBgSndyCk

--- MFBgSndyCk.g01 (geometry) --- (continued)

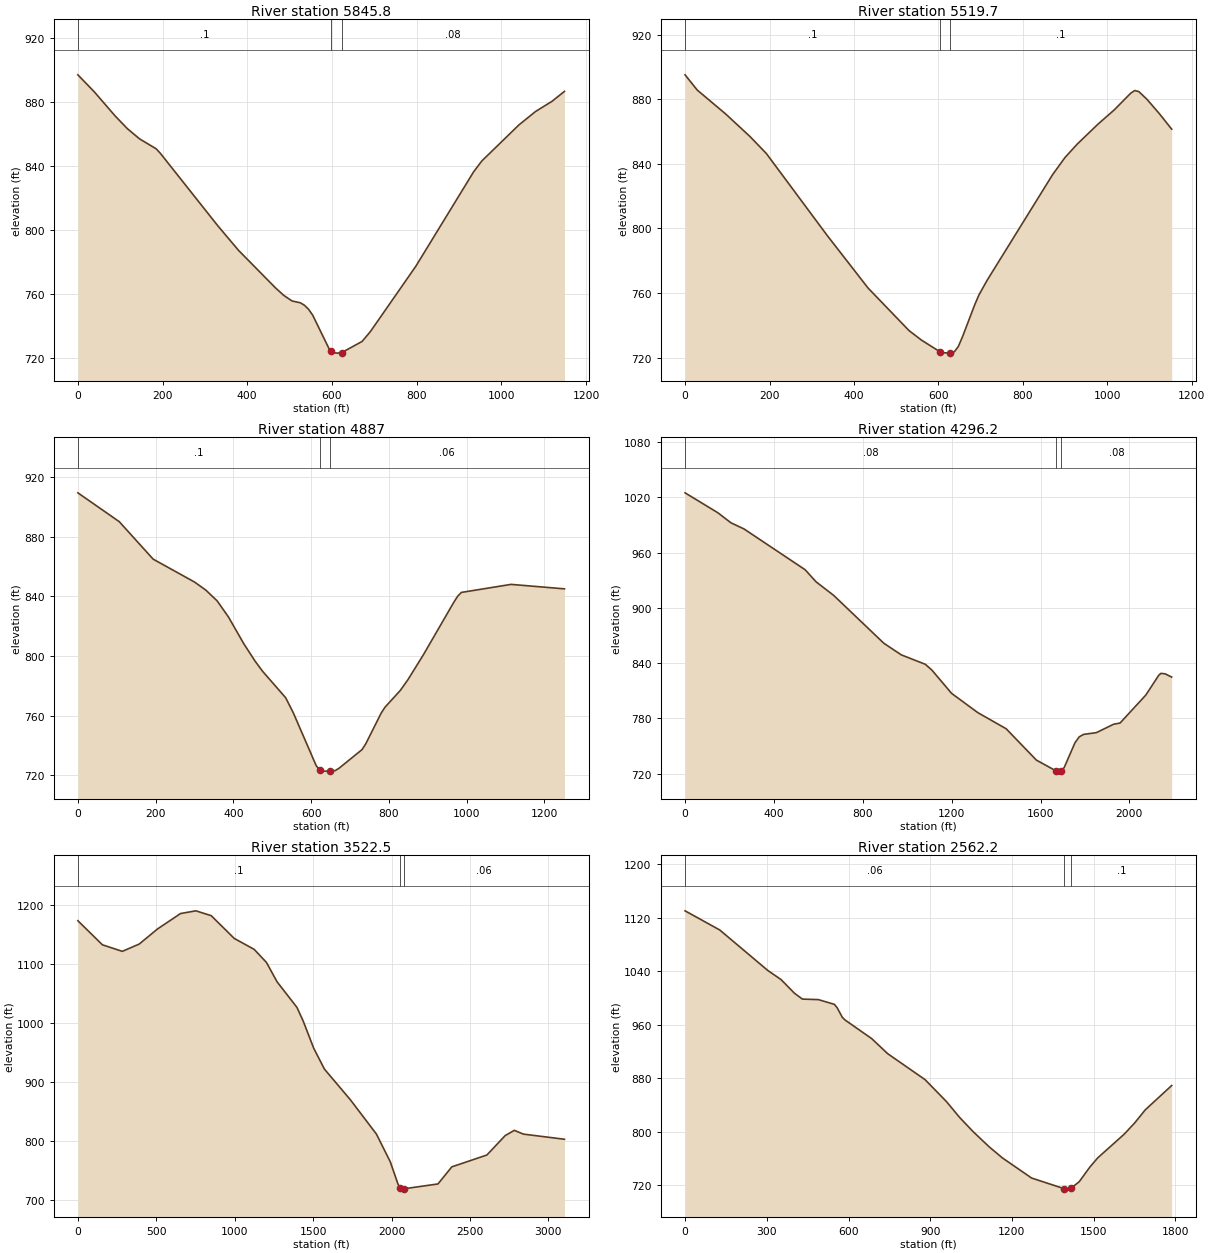
Type RM Length L Ch R = 1 ,5845.8  ,310.4,326,341.6
XS GIS Cut Line= 3
     1920701.668      581906.005     1920091.986      581969.126
     1919558.625      582024.648
#Sta/Elev= 30
       0  896.74    38.9  886.09    87.6  871.17   116.8  863.12   145.9  856.68
   184.9  850.51   194.6  847.76   330.8   802.3   379.4  787.05     467  763.52
   486.5  758.84   505.9   755.4   525.4  754.27   535.1  752.73   544.8  750.23
   554.6  746.53   593.5  725.43   597.7  724.42   603.2  723.09   612.9  722.81
   622.7  723.07   671.4  730.14   690.9   736.3   798.2  777.13   934.7  836.14
   954.2  842.96  1041.9   865.5  1080.9  873.82  1119.9  880.21  1149.2  886.41
#Mann= 3 , 0 , 0
       0      .1       0   597.7    .045       0   622.7     .08       0
Bank Sta=597.7,622.7
XS Rating Curve= 0 ,0
Exp/Cntr=0.3,0.1

Type RM Length L Ch R = 1 ,5519.7  ,651.3,632.5,613.6
XS GIS Cut Line= 3
     1920723.787      581829.392     1920318.324      581745.667
     1919657.298      581416.334
#Sta/Elev= 30
       0  895.18    28.9  885.73    96.3  870.91     154  856.91   192.6  846.43
     337  795.56   433.4  763.13   530.6  736.73   559.8  730.89   603.3  723.72
   608.4  723.12   627.8   722.8   628.3  722.84   637.5  723.55   647.2   726.9
     657  732.87   686.1  752.78   695.8  758.72   715.3  767.86   870.7  833.43
   899.9  843.98     929  852.31   977.6  864.53  1016.5  873.46  1055.4  883.77
  1065.1  885.45  1074.8  884.78  1094.2  879.96  1123.4  871.11  1152.5  861.54
#Mann= 3 , 0 , 0
       0      .1       0   603.3    .045       0   628.3      .1       0
Bank Sta=603.3,628.3
XS Rating Curve= 0 ,0
Exp/Cntr=0.3,0.1

Type RM Length L Ch R = 1 ,4887    ,569.7,590.6,611.5
XS GIS Cut Line= 3
     1920893.227      581266.457     1920547.065       581072.15
     1919714.869      581266.111
#Sta/Elev= 30
       0  909.47   106.5  890.12   193.6  864.99   300.2  849.61   329.2   844.2
   358.2     837   387.3   826.2   426.4   808.4   455.9  796.52   475.5  789.64
   534.5  772.01   554.1  761.91     613  726.44   622.5  723.32   632.7   722.8
   647.5  722.81   662.2  723.19     672   724.8   730.9  737.24   740.7  741.24
     780  761.68   789.8  765.64   829.1  776.87   848.8  784.09   888.1   800.6
   966.6  835.93   976.5  840.02   986.3  842.66    1114  848.06  1251.5  845.06
#Mann= 3 , 0 , 0
       0      .1       0   622.5    .045       0   647.5     .06       0
Bank Sta=622.5,647.5
XS Rating Curve= 0 ,0
Exp/Cntr=0.3,0.1

Type RM Length L Ch R = 1 ,4296.2  ,837.2,773.2,709.3
XS GIS Cut Line= 4
     1921436.751      581776.189     1920455.898      580661.409
      1920172.58      580495.927     1919967.666       580812.83
#Sta/Elev= 30
       0 1024.98   147.5 1003.37   206.5  992.44   265.5  985.75   540.8  941.41
     590  928.29   668.7  913.68   894.8  861.65   973.5  849.02  1081.7  838.78
  1111.2  832.48  1199.7  807.24  1317.7  786.34  1445.5  768.79  1581.4  734.78
  1668.4  723.26  1687.5   722.8  1693.4  723.11  1706.8  726.79  1755.1  753.57
  1774.4  760.05  1793.7  762.66  1851.7   764.6  1929.1  773.71  1958.1  775.02
  2074.2  805.43  2132.3  826.89    2142  828.94  2161.3  828.44  2190.4  824.93
#Mann= 3 , 0 , 0
       0     .08       0  1668.4    .045       0  1693.4     .08       0
Bank Sta=1668.4,1693.4
XS Rating Curve= 0 ,0
Exp/Cntr=0.3,0.1

Type RM Length L Ch R = 1 ,3522.5  ,926,960.3,994.5
XS GIS Cut Line= 6
     1921423.995      578740.417     1920416.139      579238.034
     1920089.185      579945.518     1920186.877      580436.359
     1919905.715      580867.633     1919803.258      581020.127
#Sta/Elev= 30
       0 1172.95   156.4  1132.2   283.4  1121.1     391 1133.42   508.2 1159.06
   654.9 1185.12   752.6 1189.68   850.3 1181.45     997 1142.99    1124 1124.48
    1202  1102.5  1270.1 1069.59  1396.8 1026.26  1435.8 1003.71    1504  956.99
  1572.2   921.8  1737.8  869.83  1903.4  811.98  1991.7  765.14  2040.8  727.43
  2053.3  721.04  2070.2  718.73  2078.3  719.28  2295.9  727.49  2384.2  756.39
  2607.8  776.46  2724.4  809.31  2782.7   818.2    2841   811.8  3102.5  803.12
#Mann= 3 , 0 , 0
       0      .1       0  2053.3    .045       0  2078.3     .06       0
Bank Sta=2053.3,2078.3
XS Rating Curve= 0 ,0
Exp/Cntr=0.3,0.1

Type RM Length L Ch R = 1 ,2562.2  ,588.8,568.2,547.6
XS GIS Cut Line= 3
     1920410.742      579222.463     1919619.788      580143.284
     1919126.564      580433.977
#Sta/Elev= 30
       0 1130.11   127.3 1101.51   303.5 1041.08   352.4 1027.37   401.4 1007.04
   430.7  998.22   489.5  997.41   548.2  990.34     558  985.46   577.6  970.86
   587.4  966.93   685.3  939.11     744  916.57     881  877.85   959.4  845.15
  1008.3  821.19  1057.3  800.19    1116  777.56  1164.9  760.87  1272.1  730.78
  1391.5  714.86  1398.3  714.18  1416.5  715.46  1446.8  725.16  1485.6  746.88
  1514.7  760.78  1611.7  796.13  1650.6  813.09  1689.4  832.64  1786.4     869
#Mann= 3 , 0 , 0
       0     .06       0  1391.5    .045       0  1416.5      .1       0
Bank Sta=1391.5,1416.5
XS Rating Curve= 0 ,0
Exp/Cntr=0.3,0.1

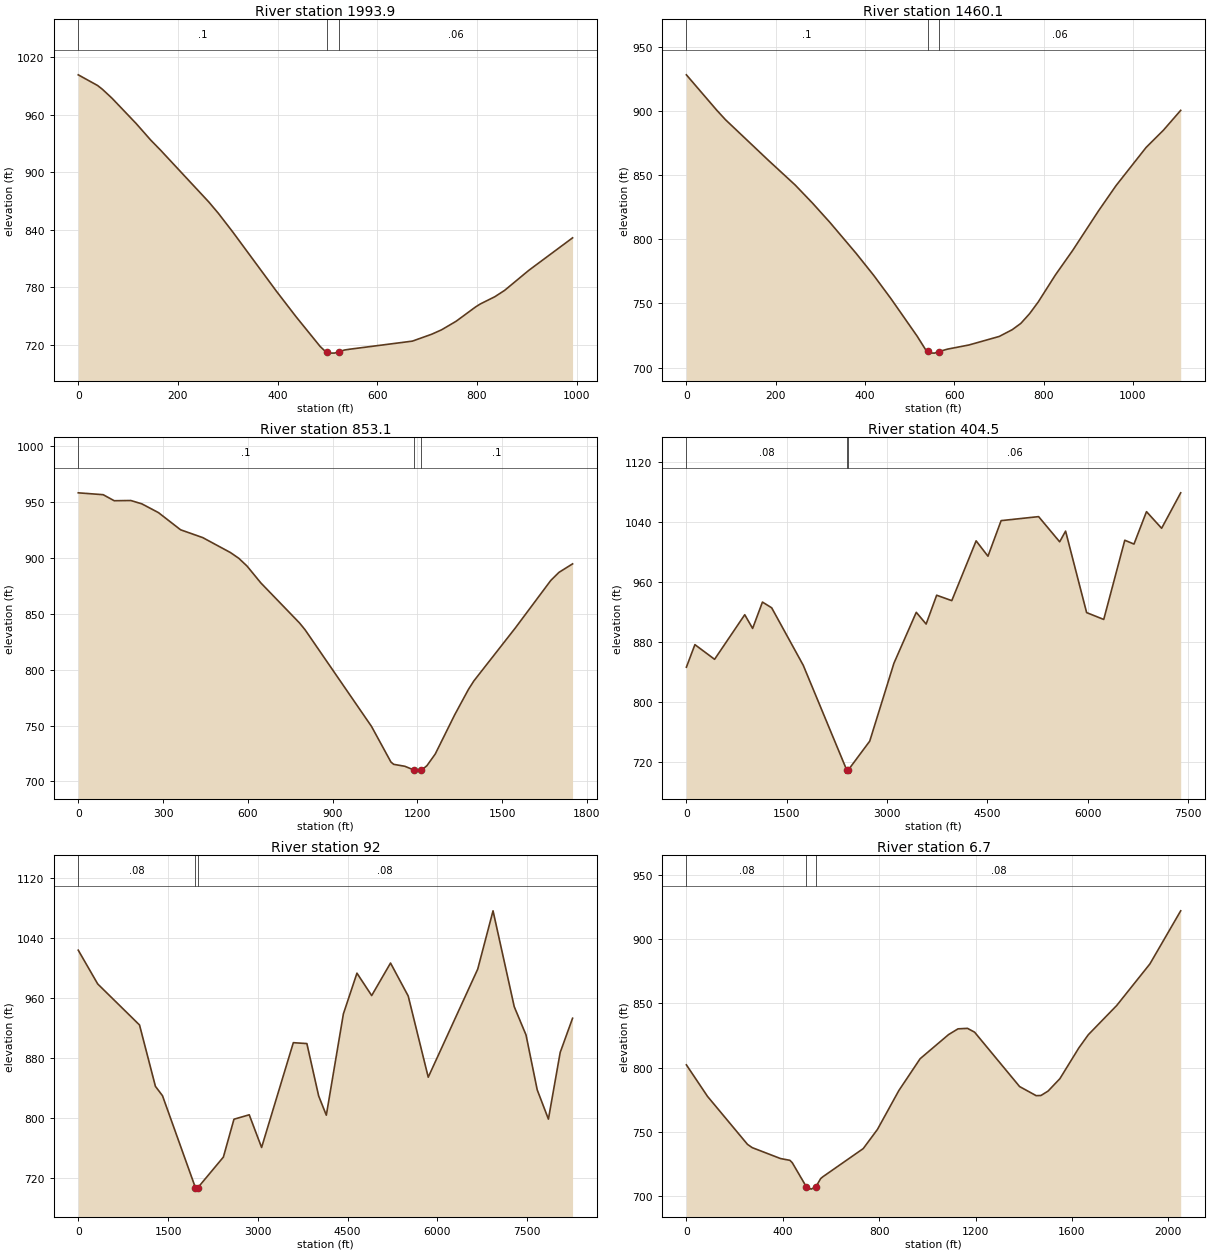
Type RM Length L Ch R = 1 ,1993.9  ,546.9,533.5,520.3
XS GIS Cut Line= 3
     1919236.349      579306.226     1919185.938      579671.112
     1919008.296      580268.852
#Sta/Elev= 30
       0 1001.34    38.8  990.21    48.5  986.25    67.8  976.93   116.3  950.53
   145.4  933.36   164.8  923.06   261.7  869.01   281.1   857.1   310.2  837.51
   397.6  775.93   436.6  749.61   485.3  718.39     495   713.6   498.6  712.79
   504.8  711.39   514.5  711.46   523.6   712.9     534   714.6   543.7   715.4
   670.4  723.88   709.4  731.11   728.9  735.64   758.1  744.54   797.1  759.44
   806.8  762.62     836  770.18   855.5  776.75   904.2  797.69   991.9  831.49
#Mann= 3 , 0 , 0
       0      .1       0   498.6    .045       0   523.6     .06       0
Bank Sta=498.6,523.6
XS Rating Curve= 0 ,0
Exp/Cntr=0.3,0.1

Type RM Length L Ch R = 1 ,1460.1  ,590.2,606.4,622.3
XS GIS Cut Line= 3
     1918519.462      579331.347     1918628.214      579876.212
     1918731.802      580417.985
#Sta/Elev= 30
       0   928.3    68.2  900.64    87.7  893.25   185.2  861.11   243.7  842.35
   282.7  828.17   321.7  813.09   380.2  789.05   419.2  772.06   458.1  753.76
   516.6  724.59   536.1   713.8   540.3  712.75   545.9  711.36   555.6  711.22
   565.3  712.36   584.6  714.32     633  717.58   700.8  724.24   729.8  729.49
   749.2  734.44   768.5  741.89   787.9  751.02   826.6  772.22   865.3  791.36
   923.3  822.28     962  841.71  1029.8  871.69  1068.5   885.1  1107.2  900.59
#Mann= 3 , 0 , 0
       0      .1       0   540.3    .045       0   565.3     .06       0
Bank Sta=540.3,565.3
XS Rating Curve= 0 ,0
Exp/Cntr=0.3,0.1

Type RM Length L Ch R = 1 ,853.1   ,448.2,448.5,448.9
XS GIS Cut Line= 4
     1918790.105      578874.525     1918206.193      579481.113
     1917940.647      580071.098     1917951.086      580331.469
#Sta/Elev= 30
       0  958.42    88.1  956.75   127.3  951.34     186  951.54   225.2  948.54
   283.9  940.69   362.2  925.32   440.6  918.32   538.5  904.95   567.8  899.87
   597.2  892.88   646.2  877.75   783.2  841.85   802.8  835.77    1038  749.19
  1106.6  717.37  1116.4  715.28  1155.7  713.55  1188.9  710.14  1204.7   709.2
  1213.9  709.86  1234.1   714.1  1263.5  724.53  1332.1  759.52  1381.1  782.44
  1400.7  790.16  1546.9   837.4  1672.3  879.92  1701.3  887.19  1749.5   894.8
#Mann= 3 , 0 , 0
       0      .1       0  1188.9    .045       0  1213.9      .1       0
Bank Sta=1188.9,1213.9
XS Rating Curve= 0 ,0
Exp/Cntr=0.3,0.1

Type RM Length L Ch R = 1 ,404.5   ,326.3,312.2,298.1
XS GIS Cut Line= 6
     1919062.219      577774.731     1918733.414      578863.187
     1917739.029      579479.518     1917639.411      579706.293
     1917912.769      580312.581     1918829.395      584379.254
#Sta/Elev= 30
       0  846.26   127.4  876.38   421.5  856.79   872.4  916.33     990     898
    1137  933.18  1274.7  925.59  1746.6  848.84  2397.6  708.75  2411.7  707.52
  2422.6  709.39  2740.4  747.54  3102.3  851.59    3436  919.52  3583.5  903.87
  3740.8  942.34  3966.9  935.12  4330.7 1014.92  4507.7  994.42  4704.3 1041.92
  5264.7 1047.27  5579.3 1013.64  5667.8 1027.94  5982.4  919.13  6238.1  910.01
  6552.7 1015.73  6690.3 1010.63  6877.1 1053.92  7103.3  1031.7  7388.4 1079.04
#Mann= 3 , 0 , 0
       0     .08       0  2397.6    .045       0  2422.6     .06       0
Bank Sta=2397.6,2422.6
XS Rating Curve= 0 ,0
Exp/Cntr=0.3,0.1

Type RM Length L Ch R = 1 ,92      ,85.4,85.4,85.4
XS GIS Cut Line= 6
     1917503.232        577542.3     1917398.842      579350.237
     1917435.723       579709.33     1917333.161      579940.305
     1916246.436      580369.866     1915475.955      584971.038
#Sta/Elev= 30
       0 1024.35   324.8  979.33  1023.6  924.57  1289.3  842.72  1407.4  830.21
  1957.3  707.58  1976.8  705.62  1996.3  707.38  2424.6  748.36  2601.4  798.87
  2856.7  804.77  3062.9  761.17  3593.2  900.97  3819.6  899.78  4016.4  829.92
  4144.4  804.26  4429.8  939.48  4656.2  993.69  4902.2  963.82  5217.2  1007.2
  5512.4  963.23  5847.1  854.93  6673.8  999.08  6929.7 1076.85    7284  948.96
  7480.9  911.25  7667.9  838.04  7854.9  799.05  8051.7  887.95  8258.4  933.58
#Mann= 3 , 0 , 0
       0     .08       0  1957.3    .045       0  1996.3     .08       0
Bank Sta=1957.3,1996.3
XS Rating Curve= 0 ,0
Exp/Cntr=0.3,0.1

Type RM Length L Ch R = 1 ,6.7     ,8.6,6.7,4.7
XS GIS Cut Line= 4
     1917367.271      579020.442     1917314.851      579357.814
     1917353.906      579748.365     1916197.226      580378.947
#Sta/Elev= 30
       0   802.2    87.8  777.67   253.6  740.39   273.1  737.87   390.5  729.38
   429.7  727.99   439.6   726.1   498.4  707.24     518  705.61   537.7  707.53
   557.3  713.83   567.1  715.32   733.9  737.11   792.9  752.02   881.4  782.14
   969.9  806.95  1087.8   825.7  1127.2  830.19  1166.5  830.57    1196  827.61
  1382.8  785.32  1451.6  778.26  1471.3  778.38  1500.8   781.8  1549.9  791.44
  1628.6  815.36  1667.9  825.62  1785.9  848.37  1923.5  880.66  2051.3  921.92
#Mann= 3 , 0 , 0
       0     .08       0   498.4    .045       0   537.7     .08       0
Bank Sta=498.4,537.7
XS Rating Curve= 0 ,0
Exp/Cntr=0.3,0.1

Chan Stop Cuts=-1
Use User Specified Reach Order=0
Composite Channel Slope=5